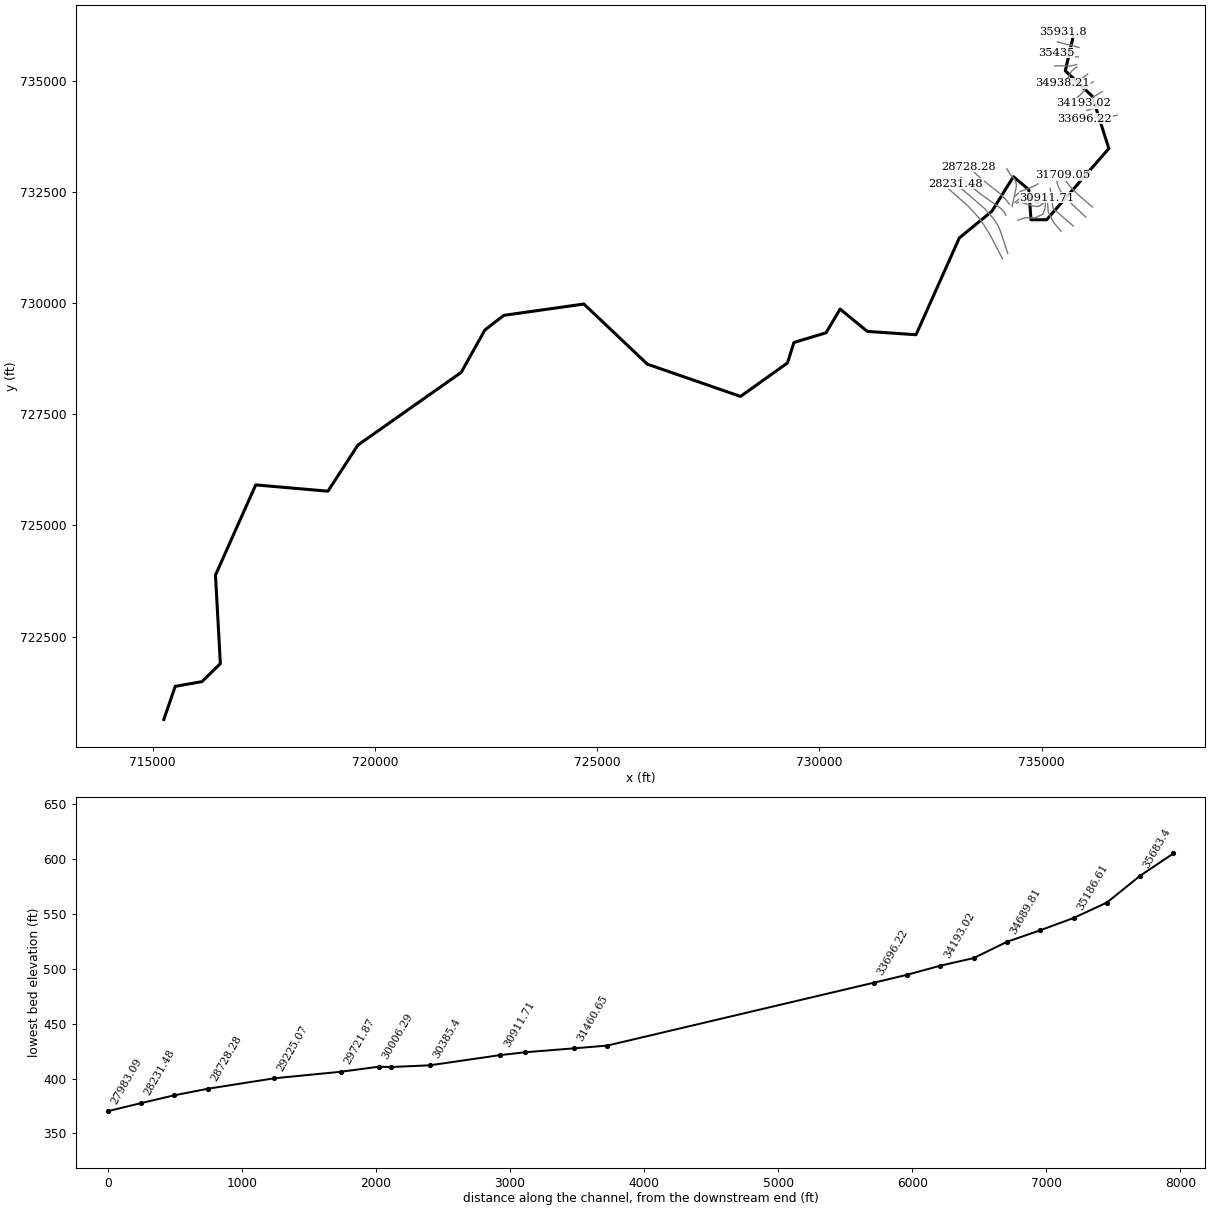
--- 4828_ras.prj (project) ---

Proj Title=4828
Current Plan=p01
Default Exp/Contr=0.3,0.1
English Units
Geom File=g01
Flow File=f01
Plan File=p01
Y Axis Title=Elevation
X Axis Title(PF)=Main Channel Distance
X Axis Title(XS)=Station
BEGIN DESCRIPTION:
RFD model 4828 exported to HEC-RAS
END DESCRIPTION:

--- 4828_ras.p01 (plan) ---

Plan Title=Plan 01
Program Version=4.10
Short Identifier=Plan 01
Geom File=g01
Flow File=f01
Subcritical Flow
Calc Critical at every XS
Secant Critical Depth

--- 4828_ras.f01 (steady flow) ---

Flow Title=Flow 01
Program Version=5.01
Number of Profiles= 6
Profile Names=10yr,25yr,50yr,100yr,100plus,500yr
River Rch & RM=4828,84, 35931.8
  745.52 1255.67 1755.18  2236.1 3264.71 4829.49
River Rch & RM=4828,84, 35683.4
  749.34 1262.48 1765.04 2249.05 3283.61 4855.33
River Rch & RM=4828,84,   35435
  832.07 1406.66 1971.21 2516.71  3674.4 5370.59
River Rch & RM=4828,84,35186.61
  834.67 1411.48 1978.35 2526.27 3688.35 5390.16
River Rch & RM=4828,84,34938.21
 1411.18 2418.26 3420.53 4400.94 6425.38 8824.41
River Rch & RM=4828,84,34689.81
 1414.12 2423.68 3428.57 4411.71 6441.09 8844.81
River Rch & RM=4828,84,34441.41
 1438.18 2466.87 3491.52 4494.78 6562.38 8996.73
River Rch & RM=4828,84,34193.02
  1446.9 2482.82 3515.04 4526.12 6608.14 9055.31
River Rch & RM=4828,84,33944.62
 1450.47 2489.39 3524.76 4539.13 6627.12 9079.76
River Rch & RM=4828,84,33696.22
 1462.96 2512.33 3558.66  4584.4 6693.22  9164.6
River Rch & RM=4828,84,31709.05
11774.9820670.6228698.2640568.4653745.3274346.92
River Rch & RM=4828,84,31460.65
11803.5820712.5828745.34 40633.853831.8774428.31
River Rch & RM=4828,84,31095.58
 11822.9 20740.9 28777.140677.8853890.2774483.21
River Rch & RM=4828,84,30911.71
11826.6920746.4628783.3440686.5353901.7374493.98
River Rch & RM=4828,84, 30385.4
11843.9420771.75 28811.740725.8853953.8774542.97
River Rch & RM=4828,84,30093.69
 11850.520781.3628822.4740740.8353973.6774561.57
River Rch & RM=4828,84,30006.29
11852.2320783.8928825.3140744.7753978.8874566.47
River Rch & RM=4828,84,29721.87
11858.79 20793.528836.0840759.72 53998.774585.08
River Rch & RM=4828,84,29225.07
11970.4420956.99 29019.241013.8154335.3174900.92
River Rch & RM=4828,84,28728.28
12011.6421017.2729086.6441107.3954459.2975017.09
River Rch & RM=4828,84,28479.88
12053.9321079.0929155.77 41203.354586.3575136.05
River Rch & RM=4828,84,28231.48
12069.8821102.4129181.8341239.4654634.2575180.89
River Rch & RM=4828,84,27983.09
12082.3721120.6529202.2341267.7554671.7475215.96
River Rch & RM=4828,84,27734.69
12164.3421240.3429335.9141453.2154917.4375445.64
River Rch & RM=4828,84,27486.29
12169.5621247.95 29344.441464.9954933.0475460.23
River Rch & RM=4828,84, 27237.9
12174.4321255.0629352.3341475.9954947.6275473.84
River Rch & RM=4828,84, 26989.5
12240.5421351.4929459.9241625.2355145.33 75658.4
River Rch & RM=4828,84,26739.52
12286.1921418.0129534.08 41728.155281.6175785.48
River Rch & RM=4828,84,26489.55
12304.6721444.9329564.0841769.7155336.7475836.87
River Rch & RM=4828,84,26239.58
12313.7421458.14 29578.841790.1355363.7975862.07
River Rch & RM=4828,84, 25989.6
12319.3221466.2729587.8541802.6955380.4375877.57
River Rch & RM=4828,84,25739.63
12326.2921476.4329599.1741818.3955401.2275896.95
River Rch & RM=4828,84,25489.66
12333.2721486.5929610.4941834.0955422.0275916.32
River Rch & RM=4828,84,25239.68
12337.4621492.6829617.28 41843.5 55434.575927.95
River Rch & RM=4828,84,24989.71
12343.7421501.8329627.4741857.6455453.2275945.38
River Rch & RM=4828,84,24739.74
12872.4822268.9230478.8943038.2457017.2977395.45
River Rch & RM=4828,84,24489.76
12918.41 22335.330552.3143140.0157152.1277519.85
River Rch & RM=4828,84,24239.79
12924.77 22344.530562.4743154.1157170.7977537.07
River Rch & RM=4828,84,23989.81
12931.8422354.7130573.7643169.7657191.53 77556.2
River Rch & RM=4828,84,23689.84
13054.6922532.0530769.6543441.2857551.2477887.55
River Rch & RM=4828,84,23459.85
13056.8122535.1230773.0443445.9757557.4677893.27
River Rch & RM=4828,84,23041.13
13093.6922588.3130831.7343527.3257665.2277992.42
River Rch & RM=4828,84,22566.06
13131.3122642.5430891.5443610.2257775.05 78093.4
River Rch & RM=4828,84,22369.28
13141.9722657.8930908.4743633.6757806.1378121.95
River Rch & RM=4828,84,22180.71
13146.5822664.54 30915.843643.8457819.5978134.33
River Rch & RM=4828,84,21990.02
13206.2922750.5331010.5843775.1957993.6178294.15
River Rch & RM=4828,84,21490.08
13357.6622968.2731250.2444107.2958433.5778697.55
River Rch & RM=4828,84, 21240.1
13369.0822984.6731268.2844132.2958466.6978727.88
River Rch & RM=4828,84,20740.16
13399.0623027.7431315.6344197.8958553.6178807.45
River Rch & RM=4828,84,20240.21
13418.3423055.4431346.0744240.0758609.4878858.58
River Rch & RM=4828,84,19740.26
16242.4427045.9235663.0150214.2766524.1385951.95
River Rch & RM=4828,84,19240.31
 16291.427114.0435735.5950314.5966657.0586068.69
River Rch & RM=4828,84,18740.37
16338.8927180.0835805.9350411.8166785.8486181.74
River Rch & RM=4828,84,18240.42
16391.7127253.4935884.0850519.8266928.9486307.25
River Rch & RM=4828,84,17740.47
 16472.927366.2836004.0650685.6567148.6286499.79
River Rch & RM=4828,84,17240.52
 16491.827392.5136031.9650724.21 67199.786544.53
River Rch & RM=4828,84,16740.58
16570.1127501.1836147.44 50883.867411.1386729.59
River Rch & RM=4828,84,16240.63
16604.5727548.96 36198.250953.9567504.0686810.88
River Rch & RM=4828,84,15740.68
 17664.729011.4537743.64 53088.870332.3489267.81
River Rch & RM=4828,84,15240.73
17676.2629027.3137760.3253111.8370362.8489294.16
River Rch & RM=4828,84,14740.79
 17813.229215.1437957.6853384.3570723.8889605.45
River Rch & RM=4828,84,14470.82
 17849.929265.4438010.4853457.2670820.4789688.64
River Rch & RM=4828,84, 14213.8
17855.6929273.3838018.8253468.7770835.7189701.77
River Rch & RM=4828,84,14001.74
 17858.429277.0838022.7153474.1470842.83 89707.9
River Rch & RM=4828,84,13383.09
   1788729316.2638063.8453530.9270918.0589772.66
River Rch & RM=4828,84,   12741
18046.8629535.08 38293.353847.7271337.7590133.58
River Rch & RM=4828,84,12277.58
32946.2148843.7557504.6780264.17106334.4118240.1
River Rch & RM=4828,84,11814.17
32977.7848882.8757541.8880315.17  106402118291.2
River Rch & RM=4828,84,11350.75
33037.7348957.1357612.5380411.97106530.2118388.1
River Rch & RM=4828,84,10887.34
33347.1349340.0257976.4480910.59107190.8118886.8
River Rch & RM=4828,84,10423.92
33376.9749376.9158011.4880958.59107254.4118934.8
River Rch & RM=4828,84,9960.509
33390.7449393.9558027.6580980.74107283.7118956.9
River Rch & RM=4828,84,9497.095
33404.5249410.9758043.82 81002.9107313.1  118979
River Rch & RM=4828,84, 9033.68
33519.8249553.4858179.0981188.22107558.6119164.1
River Rch & RM=4828,84, 8241.47
33557.0549599.4858222.7381248.01107637.8119223.7
River Rch & RM=4828,84,7900.332
33568.5549613.6858236.2181266.47107662.3119242.1
River Rch & RM=4828,84,6282.671
34602.8350888.06 59442.382918.47109850.8120885.1
River Rch & RM=4828,84,5487.456
34622.31   50912 59464.982949.42109891.8120915.8
River Rch & RM=4828,84,4858.401
34634.3650926.8259478.8882968.57109917.2120934.7
River Rch & RM=4828,84,3888.277
42340.0860236.8268123.5394791.92125580.9132401.7
River Rch & RM=4828,84, 2849.69
42390.0960296.2768177.8894866.15125679.2132472.2
River Rch & RM=4828,84, 1996.01
43780.4561944.7469680.5196918.38  128398134414.1
Boundary for River Rch & Prof#=4828,84,1
Up Type= 0
Dn Type= 2
Boundary for River Rch & Prof#=4828,84,2
Up Type= 0
Dn Type= 2
Boundary for River Rch & Prof#=4828,84,2
Up Type= 0
Dn Type= 2
Boundary for River Rch & Prof#=4828,84,2
Up Type= 0
Dn Type= 2
Boundary for River Rch & Prof#=4828,84,2
Up Type= 0
Dn Type= 2
Boundary for River Rch & Prof#=4828,84,2
Up Type= 0
Dn Type= 2

--- 4828_ras.g01 (geometry) ---

Geom Title=4828
Program Version=4.10

River Reach=4828,84
Reach XY= 30
735714.637663871  736023.0480057735532.693219453735226.520227939
 736136.85988611734655.686894596736512.126360446733478.023350507
735111.877247244731875.924163118734760.488358319731876.618607566
734711.182802767732554.396385342734364.655025005732843.979718715
733879.238358349732065.507496476733147.988358319731466.896385357
732174.377247214729289.118607581731077.849469453729364.118607566
730466.043913871729866.896385357730149.377247244729332.868607596
729427.849469453729115.507496476729281.321691692728653.701940939
 728225.76613608727901.618607581726129.932802767728627.313052014
724702.849469423729980.090829805722901.460580498  729725.2297187
722475.071691662729396.063052028721943.127247185728442.590829805
 719619.51613611726807.868607596 718944.51613605725769.674163133
717320.210580528 725911.34082979716414.655024976723882.174163163
716524.377247214721890.507496461716111.877247244721485.646385372
715509.099469453721379.396385357 715252.70288527720634.507516786

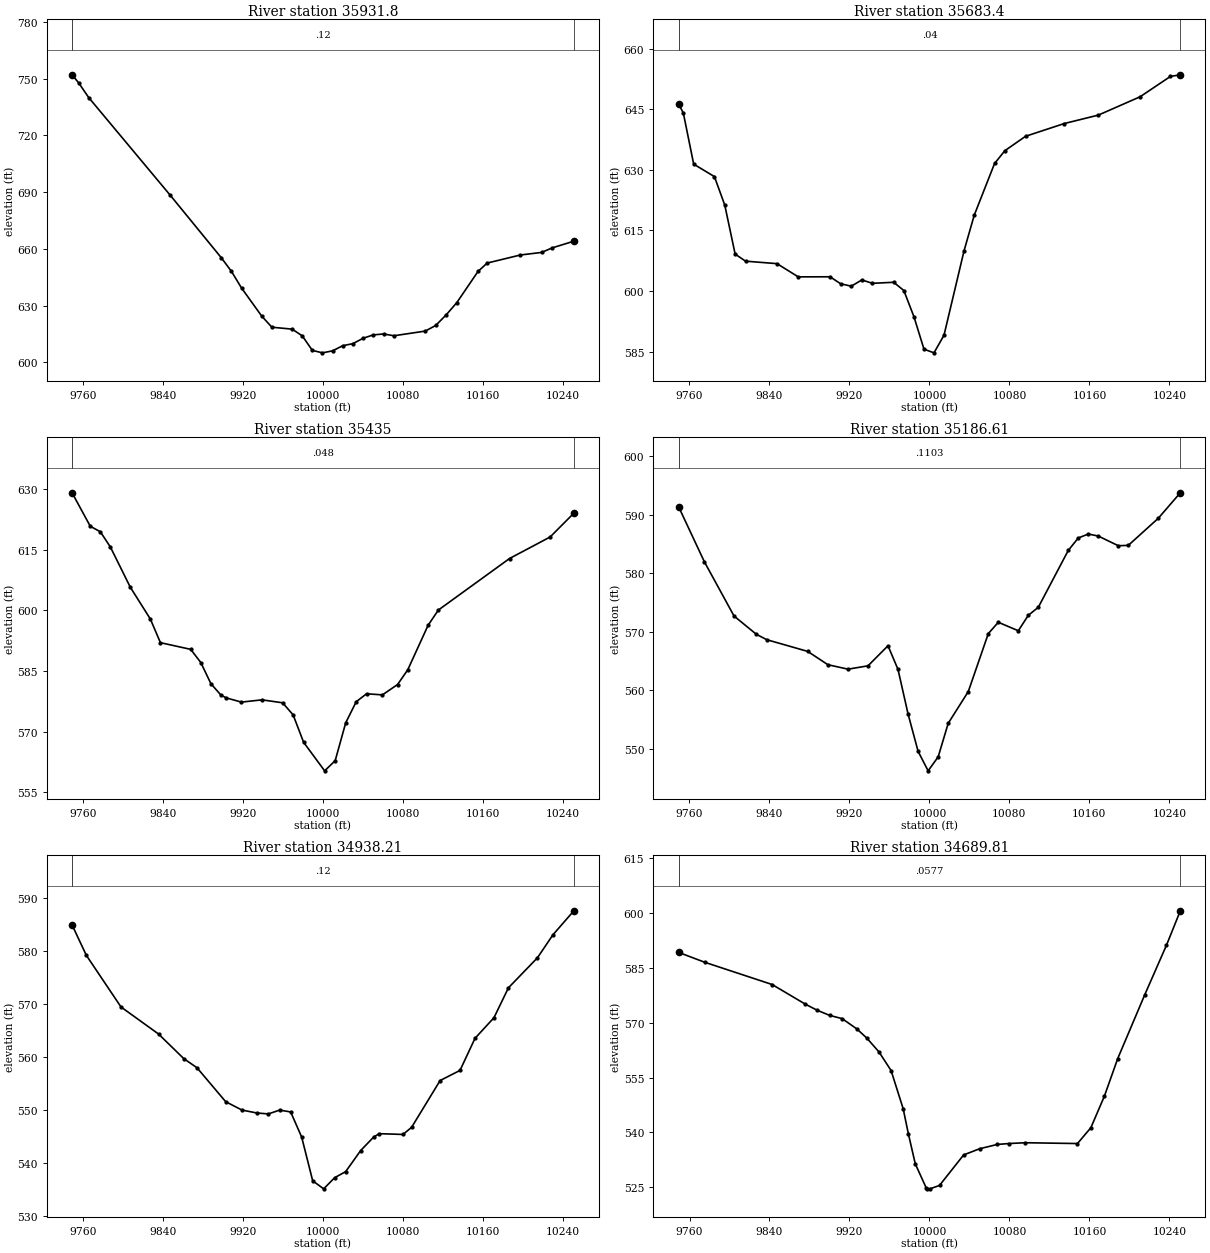
Type RM Length L Ch R = 1 , 35931.8,248.397200,248.397200,248.397200
XS GIS Cut Line= 6
735961.377834958735977.001550372735793.268158022736009.786926469
735694.813641069 736024.93396469735660.472449031736031.833073715
735601.287662273736049.151290043735474.572621502736093.860795758
#Sta/Elev= 30
9749.014752.07249755.512747.86399765.701740.00139847.208688.4049 9898.15655.4504
9908.338648.24339918.527639.3706 9938.78624.47219948.902618.63669969.144617.6223
9979.265614.07649989.386606.37679999.505605.091110009.61606.136910019.72608.8602
10029.91609.939110040.11612.783710050.31614.583710060.63615.057410071.05614.1237
10102.31 616.59210112.73619.544610123.27625.175810133.87631.627110155.08648.1075
10164.23652.5421 10197.5656.8136 10218.7658.168410229.31660.577110250.97664.1062
#Mann= 3 , 0 , 0
9749.014    0.12       09749.014    0.12       010250.97    0.12       0
#XS Ineff= 2 , 0
       0                               0
Bank Sta=9749.014,10250.97
Exp/Cntr=0.3,0.1

Type RM Length L Ch R = 1 , 35683.4,248.397300,248.397300,248.397300
XS GIS Cut Line= 6
735839.622655605735750.653725101735763.533343734 735771.35759073
735633.761148963735817.079360123735571.693305823735820.251071995
735536.850421868735826.189480616735356.418380479735877.805103143
#Sta/Elev= 30
9749.109646.33939753.899644.07919764.263631.4169 9784.99 628.3339795.354621.2784
9805.717609.15749816.081607.40649847.614606.78679868.819 603.5169900.627603.5397
9911.229601.80779921.832601.21119932.434602.75559943.037601.92079964.242602.1801
9974.427600.13979984.553593.63989994.574585.615910004.59584.715310014.59589.0704
10034.69610.024410044.84618.788910065.16631.579210075.49634.752410096.16638.3105
10134.81641.460410169.02643.559310210.71648.0919   10241653.121510250.93653.5332
#Mann= 3 , 0 , 0
9749.109    0.04       09749.109    0.04       010250.93    0.04       0
#XS Ineff= 2 , 0
       0                               0
Bank Sta=9749.109,10250.93
Exp/Cntr=0.3,0.1

Type RM Length L Ch R = 1 ,   35435,248.397200,248.397200,248.397200
XS GIS Cut Line= 6
735823.209710897735538.255714659735742.617736433735542.173181075
735669.614254878735552.304239403735619.983571089735563.887390394
735507.414693278735598.259915658735331.602803854735630.769148472
#Sta/Elev= 30
9749.074 629.1059767.305620.80849777.317619.46619787.329615.70769807.353605.7167
9827.376597.85589837.452592.0027 9867.74590.34969877.835587.09249887.931 581.856
9898.027579.01129903.464578.32359918.471577.29099939.009577.85359959.664577.1213
 9970.17574.13329980.675567.3465 10001.7560.279910012.24562.790110022.78572.1736
10033.28577.383310043.63579.354910059.49579.081610074.63581.637410084.84585.2891
10105.25596.333510115.45600.078210186.65612.835710227.24618.161610250.98624.0565
#Mann= 3 , 0 , 0
9749.074   0.048       09749.074   0.048       010250.98   0.048       0
#XS Ineff= 2 , 0
       0                               0
Bank Sta=9749.074,10250.98
Exp/Cntr=0.3,0.1

Type RM Length L Ch R = 1 ,35186.61,248.397200,248.397200,248.397200
XS GIS Cut Line= 6
735789.809029365735370.432072738735697.515312883735343.742387639
735623.535404585 735332.47937038735578.077002745735332.419324225
735453.188643474735341.010766703735293.002019963 735337.59655583
#Sta/Elev= 30
9749.077591.42439774.902 581.9899804.628572.70019826.951569.58149837.361568.6586
9878.287 566.6589898.468564.38259918.582563.62219938.591564.19219958.591567.6271
9968.603563.57499978.643 555.9679988.683549.57779998.723546.235810008.77548.6264
10018.82554.364110038.89559.789110058.91569.700310068.91571.639710088.93570.1892
10098.93 572.83310108.93574.202910138.93583.935110148.93586.054610158.93586.7305
10168.93586.382210188.95  584.7310198.95584.790510228.97589.429110250.98593.7837
#Mann= 3 , 0 , 0
9749.077  0.1103       09749.077  0.1103       010250.98  0.1103       0
#XS Ineff= 2 , 0
       0                               0
Bank Sta=9749.077,10250.98
Exp/Cntr=0.3,0.1

Type RM Length L Ch R = 1 ,34938.21,248.397200,248.397200,248.397200
XS GIS Cut Line= 6
735796.712702584735312.414133289735728.939454965735268.674237139
735674.486817431735219.180331871735582.147073314735053.519361291
735538.299032351735001.155863394735472.560275653 734941.56034103
#Sta/Elev= 30
9749.099584.90069763.379579.15269798.055569.39759835.572564.29429860.837559.6457
9874.011557.92739902.758551.50689918.993549.93469933.609  549.399945.389549.2006
9956.704549.92699967.719549.57499978.735544.8242 9989.75536.570310000.72535.0539
10011.69537.156710022.67538.294110037.74542.284810050.94544.876410056.42545.4718
10080.03545.325710088.67546.6736 10117.2555.510610137.06557.417910152.09563.4839
10171.06567.378410185.51573.022910214.45578.676610230.02583.029610250.94587.5686
#Mann= 3 , 0 , 0
9749.099    0.12       09749.099    0.12       010250.94    0.12       0
#XS Ineff= 2 , 0
       0                               0
Bank Sta=9749.099,10250.94
Exp/Cntr=0.3,0.1

Type RM Length L Ch R = 1 ,34689.81,248.397200,248.397200,248.397200
XS GIS Cut Line= 6
736035.811234882735151.253698145735893.259342762735044.048876037
 735832.50544205735002.479043039735767.207988511734958.392027573
735723.052901669734921.627216978735638.382434147734845.746532436
#Sta/Elev= 30
9749.019589.27219775.059586.57649842.613580.47199875.888575.08589887.669573.4264
9900.181572.01679912.694571.12719927.384568.30939937.384565.79369949.492562.0242
9961.599 556.9269973.707546.4774 9978.91539.60249985.814531.37389996.647524.8612
9997.922 524.528   10001524.575110010.06525.462210034.19533.809810050.11535.4977
10067.98  536.6910079.79536.934810095.67537.152310148.06536.928410161.49541.2807
10174.91549.847210188.34560.2086 10215.2 577.56410237.08591.228810250.94600.6568
#Mann= 3 , 0 , 0
9749.019  0.0577       09749.019  0.0577       010250.94  0.0577       0
#XS Ineff= 2 , 0
       0                               0
Bank Sta=9749.019,10250.94
Exp/Cntr=0.3,0.1

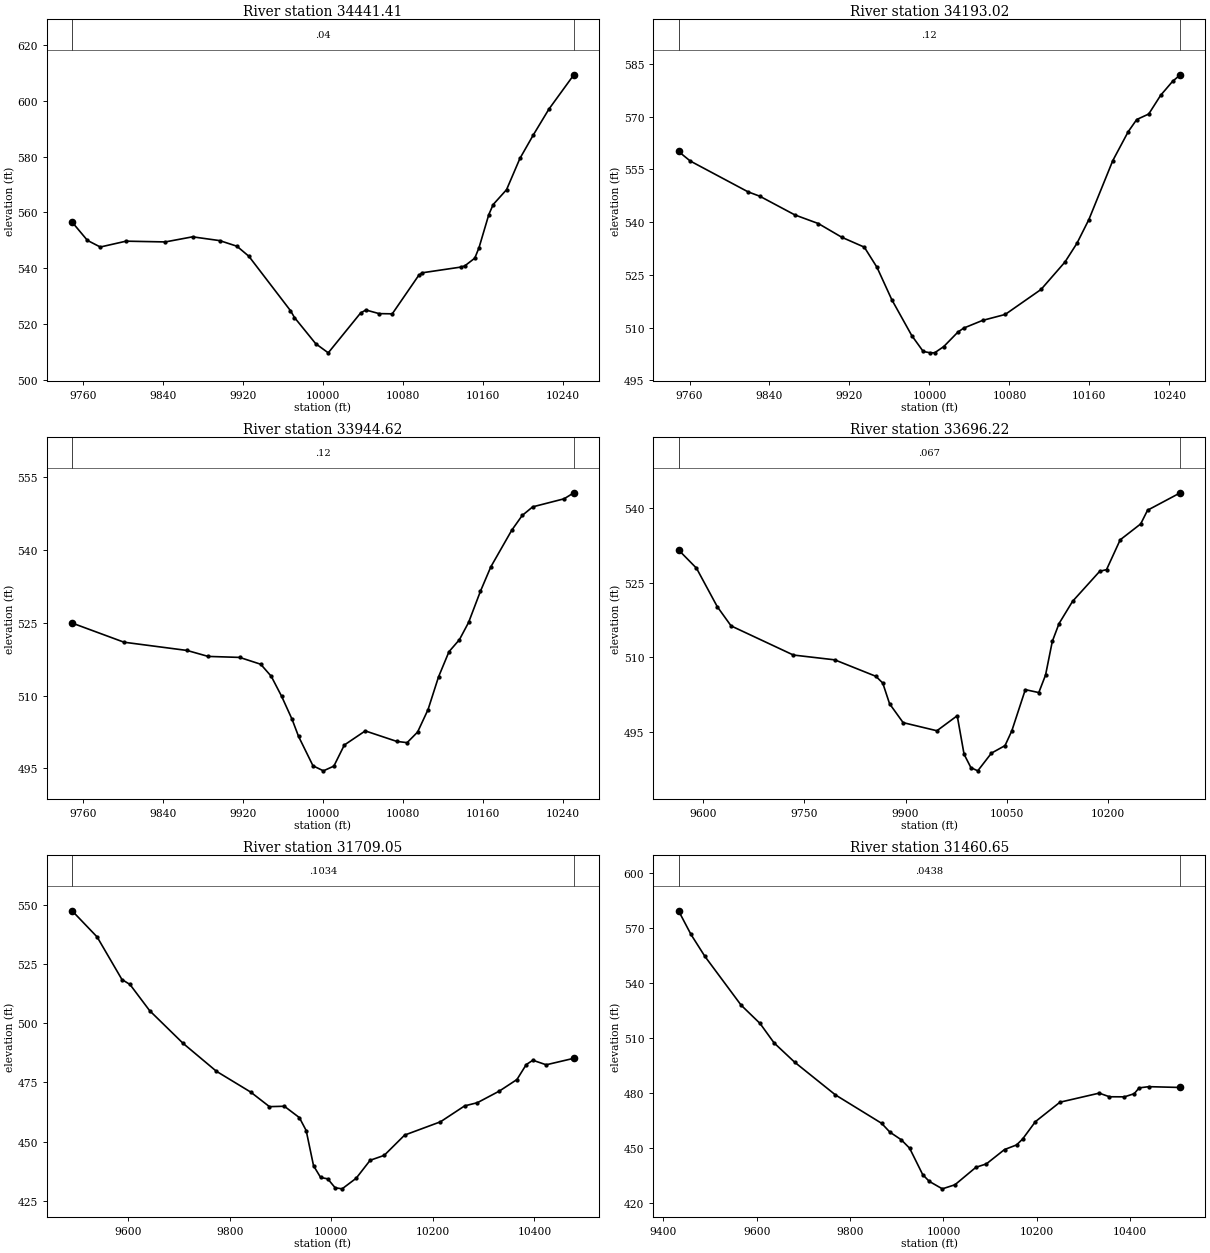
Type RM Length L Ch R = 1 ,34441.41,248.397200,248.397200,248.397200
XS GIS Cut Line= 6
736156.936633018734983.582681616736040.124191878734882.724647964
736002.954143641734842.166183125735916.806400289 734734.35611666
735865.008846395734681.906242571735804.620463371734628.377979505
#Sta/Elev= 30
9749.055556.56269764.424549.9954  9777.3547.62449803.051549.72179842.299549.4477
 9869.56551.27549896.821549.91349913.945547.91029925.852544.32779967.524524.8219
9971.524522.36239992.761512.9868 10005.3509.715310037.67524.000110042.94525.0694
10056.13523.767110069.32523.6869 10095.7537.426210099.12538.3829 10137.8540.4322
10141.81540.848710151.86543.636110156.04547.333410165.91559.270410170.27562.8445
10183.63568.1622   10197579.358610210.36587.7507 10225.9596.970110250.96609.3294
#Mann= 3 , 0 , 0
9749.055    0.04       09749.055    0.04       010250.96    0.04       0
#XS Ineff= 2 , 0
       0                               0
Bank Sta=9749.055,10250.96
Exp/Cntr=0.3,0.1

Type RM Length L Ch R = 1 ,34193.02,248.397200,248.397200,248.397200
XS GIS Cut Line= 6
736365.107976433734760.725071161736299.815757027734722.644075644
736182.410697357734650.646956124736148.707545287734631.658436427
736113.627911908734611.380574831735938.560509879734496.376182107
#Sta/Elev= 30
9749.007560.05949760.708557.34689818.591 548.5729830.242547.34169865.434 542.009
9888.895539.55789912.356535.6569 9934.86532.84989947.548527.10529962.315517.9267
 9982.31507.71379993.794 503.187   10001 502.79710005.28502.8229 10014.3504.5726
10028.38508.670910034.29 509.83710053.14512.017810075.77513.708810111.67520.8267
10135.59528.624510147.56533.945810159.52540.711610183.45557.479410198.85565.6869
10207.38569.147110219.35 570.70210231.31576.038410243.28580.011710250.98581.8664
#Mann= 3 , 0 , 0
9749.007    0.12       09749.007    0.12       010250.98    0.12       0
#XS Ineff= 2 , 0
       0                               0
Bank Sta=9749.007,10250.98
Exp/Cntr=0.3,0.1

Type RM Length L Ch R = 1 ,33944.62,248.397200,248.397200,248.397200
XS GIS Cut Line= 5
736494.445910084734484.601723783736298.758621365734420.935384015
736256.386873924734408.306470921736254.461905993734407.763793792
736015.638987173  734333.8723484
#Sta/Elev= 30
9749.003524.9327    9801520.98289864.095519.28429885.127518.05839916.675517.8529
9937.707516.44589948.223513.97239958.708509.81529969.143505.08039975.566501.5854
9990.012495.530110000.44 494.489 10010.9 495.46410021.37499.806810042.31502.7148
10073.71500.558110084.18500.293810094.65502.474810105.11507.102710115.58513.8277
10126.05519.024510136.52521.511310145.68525.057910157.45531.442110167.92536.5063
10188.86544.055610199.32547.089910209.79548.863410241.19550.520410250.99551.7634
#Mann= 3 , 0 , 0
9749.003    0.12       09749.003    0.12       010250.99    0.12       0
#XS Ineff= 2 , 0
       0                               0
Bank Sta=9749.003,10250.99
Exp/Cntr=0.3,0.1

Type RM Length L Ch R = 1 ,33696.22,1987.177700,1987.177700,1987.177700
XS GIS Cut Line= 6
736700.931871534 734228.63338659736397.513459571734163.041612322
736326.368929003734158.412676129736176.040731161734174.938439571
736085.713415074734167.933318958735967.389388747734146.355800004
#Sta/Elev= 30
9563.221 531.5449589.842527.8852 9620.64520.17949641.172516.31959733.565  510.48
 9794.94509.51699855.943506.2174 9866.11504.87019876.248500.71299896.354496.9336
 9946.45495.30559976.582498.31519986.726490.6029 9996.87487.916710007.03487.2729
10027.34490.821710047.48492.329910057.54495.283410077.57503.544810097.58502.9582
10107.59506.4667 10117.6513.211210127.61516.793710147.67521.243810187.91  527.26
10198.04527.5989 10218.3533.569310248.69536.756810258.89539.501810307.49542.9977
#Mann= 3 , 0 , 0
9563.221   0.067       09563.221   0.067       010307.49   0.067       0
#XS Ineff= 2 , 0
       0                               0
Bank Sta=9563.221,10307.49
Exp/Cntr=0.3,0.1

Type RM Length L Ch R = 1 ,31709.05,248.397200,248.397200,248.397200
XS GIS Cut Line= 6
736143.152494443732162.739458851735833.488725811732427.808897451
735679.545371771732584.131775737735607.418038338732666.766481444
735543.922003895732749.823664248735468.792416036732875.634613618
#Sta/Elev= 30
9489.483547.40439538.812536.35399587.705518.37789603.481516.29579642.319 505.218
9708.046 491.4469773.758479.6414 9841.16470.87349878.112464.72049907.481464.8827
9936.991460.10079950.435454.64159964.937439.78049978.909434.81319992.882434.2401
10007.43430.482410021.23430.020510048.83434.477910076.42442.076410104.02444.1426
10144.32452.712810214.78458.311410262.44465.032710287.62466.393910330.87471.2991
10365.48476.169710383.76482.477810396.78484.299910423.08482.389310477.52485.1331
#Mann= 3 , 0 , 0
9489.483  0.1034       09489.483  0.1034       010477.52  0.1034       0
#XS Ineff= 2 , 0
       0                               0
Bank Sta=9489.483,10477.52
Exp/Cntr=0.3,0.1

Type RM Length L Ch R = 1 ,31460.65,365.065500,365.065500,365.065500
XS GIS Cut Line= 6
 735994.02452615731937.032263576735659.976705164 732246.89411287
735470.308515817732455.673963889735425.341430545732520.068581447
735373.435403764 732622.53709884735337.548066258732761.254007965
#Sta/Elev= 30
 9432.36579.20879459.026566.29339488.708554.37969566.373527.73389606.973517.7365
9637.121507.10589681.009496.63459768.538478.75579867.374463.27219885.245458.4259
9909.376454.30959927.413449.68579955.453435.27739969.473431.59049997.512427.5129
10024.51429.729510069.44439.260110091.85441.119110130.72448.951610156.51451.4612
 10169.4454.661810197.01464.1968 10249.5474.775710333.57479.724110355.53 477.749
10387.62477.701510408.65479.423210419.04482.592910439.82 483.25210507.37 482.815
#Mann= 3 , 0 , 0
 9432.36  0.0438       0 9432.36  0.0438       010507.37  0.0438       0
#XS Ineff= 2 , 0
       0                               0
Bank Sta=9432.36,10507.37
Exp/Cntr=0.3,0.1

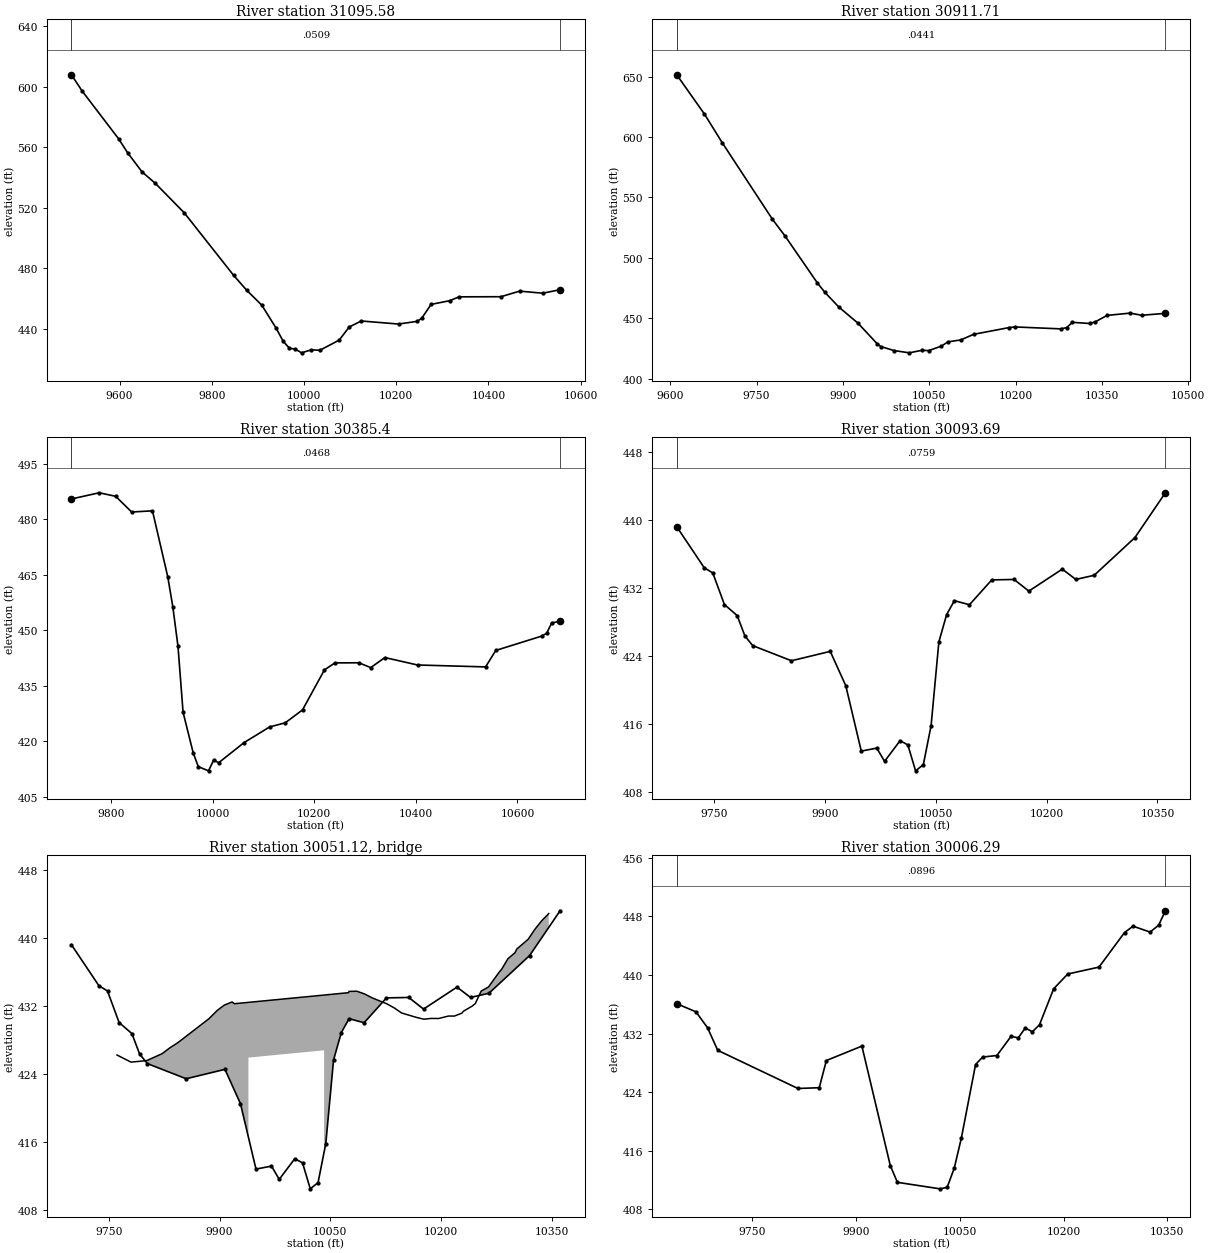
Type RM Length L Ch R = 1 ,31095.58,183.872300,183.872300,183.872300
XS GIS Cut Line= 3
735712.407786191731734.771157742735256.852230608732129.215602204
735192.963341773 732581.99337998
#Sta/Elev= 30
9495.625608.02039518.652597.36949598.018565.62099618.191   556.19648.745 543.768
9677.383536.22089740.407 516.6319847.346475.27929875.798465.37929908.454455.5239
9939.008440.57889955.164431.46759968.391427.03559981.619426.32369994.847423.9368
10015.39425.903110034.53425.6342 10076.5432.385910098.22441.072710124.26445.0244
10205.05443.000210245.45444.768710255.55446.868710275.74456.011310316.14458.4519
10336.34461.005310427.23461.095110467.63464.778510518.12463.417610555.48  465.75
#Mann= 3 , 0 , 0
9495.625  0.0509       09495.625  0.0509       010555.48  0.0509       0
#XS Ineff= 2 , 0
       0                               0
Bank Sta=9495.625,10555.48
Exp/Cntr=0.3,0.1

Type RM Length L Ch R = 1 ,30911.71,526.312400,526.312400,526.312400
XS GIS Cut Line= 4
735435.933789762 731617.75276165735263.017123102731824.002761651
735148.433789731732055.252761632735123.433789732 732376.08609499
#Sta/Elev= 30
9611.265651.51929659.413619.02919690.544 595.1529777.316532.08049799.499518.0572
9855.613479.25249868.662 471.4719892.683 459.3749926.164 445.9459959.645428.8344
9966.038 426.5779988.561423.275210015.45421.373210037.77423.534710048.93423.1922
10071.25426.958210082.41430.456910104.73 432.04310127.05436.689210188.39442.2451
10198.42442.819410278.66441.209610288.69442.248910298.72446.621610328.81445.6627
10338.84447.0995 10358.9452.349410399.03454.251810419.09452.4736 10460.3454.0542
#Mann= 3 , 0 , 0
9611.265  0.0441       09611.265  0.0441       0 10460.3  0.0441       0
#XS Ineff= 2 , 0
       0                               0
Bank Sta=9611.265,10460.3
Exp/Cntr=0.3,0.1

Type RM Length L Ch R = 1 , 30385.4,291.704600,291.704600,291.704600
XS GIS Cut Line= 6
 734468.35429212 731861.66502333734612.374874563 731920.09479855
734851.365598262 731919.22032915735025.517123045731999.002761678
735079.683789728732140.669428293735088.017123102732361.502761648
#Sta/Elev= 30
9722.037485.46999776.695 487.1419809.163486.19029840.565481.95069881.579482.2644
9911.737464.4225 9921.79456.20869931.829445.63859941.829427.84179961.829 416.863
9971.829 413.1729991.891412.046710001.94414.927810011.97414.245910062.08419.6946
10112.13423.895310143.05425.024410176.89428.503310220.16439.323410240.84441.1964
10287.75441.230110311.19439.930510339.02442.640310403.25440.633110537.24440.1143
10557.25444.558410647.32448.421410657.32449.169410667.33451.960910683.85452.4604
#Mann= 3 , 0 , 0
9722.037  0.0468       09722.037  0.0468       010683.85  0.0468       0
#XS Ineff= 2 , 0
       0                               0
Bank Sta=9722.037,10683.85
Exp/Cntr=0.3,0.1

Type RM Length L Ch R = 1 ,30093.69,87.399100,87.399100,87.399100
XS GIS Cut Line= 6
734442.823248774732249.029021993734498.543504745732281.522361711
734801.296675116 732185.11837998734877.685563982732176.785046637
734940.185563982732176.785046637735052.600456387732259.419428319
#Sta/Elev= 30
 9699.65439.22689736.898434.39169748.474433.78079764.153430.06889781.423428.7685
9791.918426.36619802.413425.23339854.886423.4498 9907.36424.55559928.349420.5192
9949.339412.82129970.328413.17149980.823411.611910001.81414.040910012.31413.5516
 10022.8410.4966 10033.3 411.22510043.79415.821510054.29425.659410064.78428.8795
10075.28430.521810095.67430.040910125.85432.964610156.02433.017210176.04431.6481
10221.23434.232610239.61433.020710264.43433.507110319.52 437.94410360.74443.2169
#Mann= 3 , 0 , 0
 9699.65  0.0759       0 9699.65  0.0759       010360.74  0.0759       0
#XS Ineff= 2 , 0
       0                               0
Bank Sta=9699.65,10360.74
Exp/Cntr=0.3,0.1

Type RM Length L Ch R = 3 ,30051.12,,,
BEGIN DESCRIPTION:
END DESCRIPTION:
Bridge Culvert--1,0,-1,-1, 0
Deck Dist Width WeirC Skew NumUp NumDn MinLoCord MaxHiCord MaxSubmerge Is_Ogee
27.295400,32.808300,2.6,0, 44, 43, , , 0.95, 0, 0,0,,
 9761.38 9780.24 9801.29 9822.33 9833.00 9843.38 9885.48 9897.19 9906.53 9917.05
 9920.14 9939.14 9939.1410041.5010041.5010074.5410075.2510085.8010096.2510106.27
10126.3210136.3410146.3610166.4110176.4310186.4510196.4710209.8310217.8710228.07
10229.9210241.9710245.9910254.0310263.9010278.1310281.8110290.1910299.7310302.24
10317.6410326.3410335.5510345.43
  426.24  425.41  425.58  426.40  427.10  427.68  430.50  431.51  432.12  432.49
  432.28  432.44  432.44  433.30  433.30  433.58  433.73  433.75  433.43  432.98
  432.27  431.79  431.19  430.67  430.46  430.55  430.54  430.83  430.83  431.18
  431.39  432.01  432.29  433.77  434.25  435.97  436.35  437.58  438.28  438.72
  439.87  441.00  442.01  442.89
 -573.76 -574.59 -574.42 -573.60 -572.90 -572.32 -569.50 -568.49 -567.88 -567.51
 -567.72 -567.56  425.94  426.80 -566.70 -566.42 -566.27 -566.25 -566.57 -567.02
 -567.73 -568.21 -568.81 -569.33 -569.54 -569.45 -569.46 -569.17 -569.17 -568.82
 -568.61 -567.99 -567.71 -566.23 -565.75 -564.03 -563.65 -562.42 -561.72 -561.28
 -560.13 -559.00 -557.99 -557.11
 9761.38 9780.24 9801.29 9822.33 9833.00 9843.38 9885.48 9897.19 9906.53 9917.05
 9920.14 9953.14 9953.1410055.5010055.5010074.5410075.2510086.3310096.2510106.27
10126.3210136.3410146.3610176.4310186.4510196.4710209.8310217.8710228.0710229.92
10241.9710245.9910254.0310263.9010278.1310281.8110290.1910299.7310302.2410317.64
10326.3410335.5510345.43
  426.24  425.41  425.58  426.40  427.10  427.68  430.50  431.51  432.12  432.49
  432.28  432.56  432.56  433.42  433.42  433.58  433.73  433.74  433.43  432.98
  432.27  431.79  431.19  430.46  430.55  430.54  430.83  430.83  431.18  431.39
  432.01  432.29  433.77  434.25  435.97  436.35  437.58  438.28  438.72  439.87
  441.00  442.01  442.89
 -573.76 -574.59 -574.42 -573.60 -572.90 -572.32 -569.50 -568.49 -567.88 -567.51
 -567.72 -567.44  426.06  426.92 -566.58 -566.42 -566.27 -566.26 -566.57 -567.02
 -567.73 -568.21 -568.81 -569.54 -569.45 -569.46 -569.17 -569.17 -568.82 -568.61
 -567.99 -567.71 -566.23 -565.75 -564.03 -563.65 -562.42 -561.72 -561.28 -560.13
 -559.00 -557.99 -557.11
BR Coef=-1 , 0 , 0 ,, 0 ,,,0.8,0,1,0,
WSPro=,,,, 1 ,,,, 0 ,,,, 0 ,,,,-1 ,-1 ,-1 , 0 , 0 , 0 , 0 , 0
BC Design=,, 0 ,, 0 ,,,,,,

Type RM Length L Ch R = 1 ,30006.29,284.426500,284.426500,284.426500
XS GIS Cut Line= 5
734400.605384707732267.285395652734500.562660426732349.790726513
734888.796675086732258.729491115734944.352230638732269.840602234
735042.963341773732340.673935547
#Sta/Elev= 30
9640.781436.0906 9668.61 434.9769685.379432.80019700.028429.72279816.034424.5107
9846.848424.6159 9857.12428.33029908.477430.29689949.562413.97779959.834 411.697
10021.46410.807910031.73411.0076   10042413.626710052.28417.738110072.82427.7793
10083.09428.804910103.63429.012110124.18431.636210134.45431.423110144.72432.7683
10154.99432.256810165.26433.215410185.69438.118310206.08440.140510251.24441.0843
10288.18445.801410300.49446.671810325.11445.866610337.43 446.79810347.23448.7751
#Mann= 3 , 0 , 0
9640.781  0.0896       09640.781  0.0896       010347.23  0.0896       0
#XS Ineff= 2 , 0
       0                               0
Bank Sta=9640.781,10347.23
Exp/Cntr=0.3,0.1

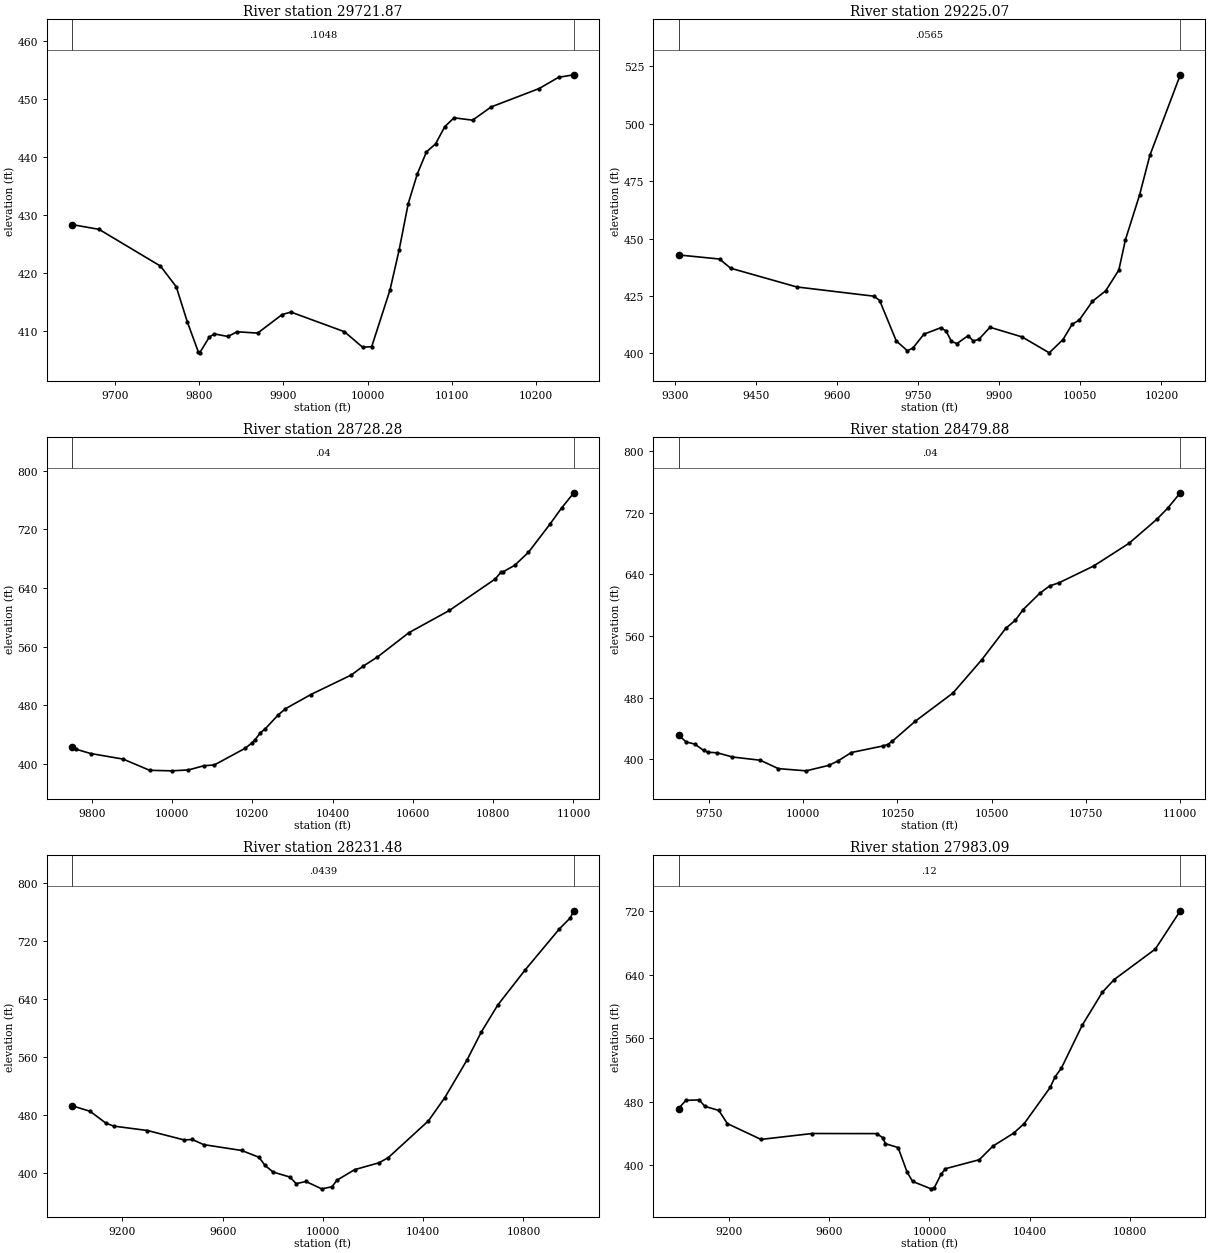
Type RM Length L Ch R = 1 ,29721.87,496.794400,496.794400,496.794400
XS GIS Cut Line= 6
734400.517123103732407.336095035734525.561827481  732512.8727559
734680.557775348732570.160553396734784.188972086732613.217585281
734842.558965892732640.192991599734920.075130314732685.452447489
#Sta/Elev= 30
  9649.2428.34179681.238 427.5169754.109421.16619772.837417.58779785.922411.5329
9799.008406.32179800.622406.17569812.093408.91229818.067409.4484  9834.1409.0021
9845.043409.8168 9869.42409.58659898.362412.79229908.929413.21699972.332409.8286
9993.844407.151810004.69407.243510026.34417.011610037.17423.9066   10048431.9514
10058.82437.101810069.65440.901810080.48442.293510091.32445.249610102.33446.7973
10124.37446.3849 10146.4448.672310203.36451.853810226.37453.795510244.54454.2331
#Mann= 3 , 0 , 0
  9649.2  0.1048       0  9649.2  0.1048       010244.54  0.1048       0
#XS Ineff= 2 , 0
       0                               0
Bank Sta=9649.2,10244.54
Exp/Cntr=0.3,0.1

Type RM Length L Ch R = 1 ,29225.07,496.794400,496.794400,496.794400
XS GIS Cut Line= 6
734334.861489892732170.535046652734434.861489922732645.535046637
734417.036266208732741.791254729 734375.54303804732801.209253863
734318.111781687732865.191020548734215.397714466733021.249013528
#Sta/Elev= 30
9306.338442.88559382.297441.09899402.698437.09629525.107428.94019668.398424.8923
9678.633 423.0189709.338405.41769729.808401.15599740.043402.28559760.513408.3508
9791.218411.12149801.392409.81099811.562405.16579821.732404.24869842.072407.6639
9852.242405.39329862.412406.17089882.752411.36029942.153407.16529992.477400.2241
 10017.9 406.00310034.96412.696110047.95414.459510072.41422.672210096.85427.2208
10121.29436.290610133.51 449.52410159.67468.989410178.72486.258510235.11521.3842
#Mann= 3 , 0 , 0
9306.338  0.0565       09306.338  0.0565       010235.11  0.0565       0
#XS Ineff= 2 , 0
       0                               0
Bank Sta=9306.338,10235.11
Exp/Cntr=0.3,0.1

Type RM Length L Ch R = 1 ,28728.28,248.397200,248.397200,248.397200
XS GIS Cut Line= 6
734272.472460628732226.264895201734217.793465108732302.455615267
734070.425617784732457.792992771733671.043937653732773.787830755
733515.976573169732911.921464205733352.840976983733066.316851631
#Sta/Elev= 30
9751.195423.17799761.526420.12189797.231414.30399878.538 406.6439944.306 391.409
9998.998390.658110040.97 391.89510079.36397.5771 10105.4398.652910181.94421.3064
10198.45428.400810207.25 433.29310219.81442.387510232.38448.050710264.51466.8892
10282.64475.372510345.47494.615810446.92521.509410476.19533.4531 10511.7545.9199
10590.14579.151910690.75609.4264 10805.2652.435910818.97661.408310824.44662.0823
10853.54671.016910887.81688.769510940.83726.744810970.43749.322211000.94770.0039
#Mann= 3 , 0 , 0
9751.195    0.04       09751.195    0.04       011000.94    0.04       0
#XS Ineff= 2 , 0
       0                               0
Bank Sta=9751.195,11000.94
Exp/Cntr=0.3,0.1

Type RM Length L Ch R = 1 ,28479.88,248.397200,248.397200,248.397200
XS GIS Cut Line= 6
734196.539372027731976.618402719734142.959957659 732066.07035166
734057.395739108732150.156630903733629.136583388732450.926148653
733430.796886951732611.197599754733182.635182381732826.522642136
#Sta/Elev= 30
 9669.18430.98799689.515422.32059712.394419.43699735.857411.23659747.589408.8807
9772.383408.12799812.089402.71339886.014 398.5079934.039387.5935 10007.8384.7178
10067.82 391.80910091.83397.415410127.84  408.5310211.87417.057310223.88418.8981
10235.97422.985710297.63449.2539 10397.5 485.83210473.64528.867910537.47  569.81
10563.37580.589810583.96594.387610628.12 615.54210654.02625.000610680.04 629.359
10770.55650.827310864.48680.297110938.21711.462810968.44726.634611000.98746.1017
#Mann= 3 , 0 , 0
 9669.18    0.04       0 9669.18    0.04       011000.98    0.04       0
#XS Ineff= 2 , 0
       0                               0
Bank Sta=9669.18,11000.98
Exp/Cntr=0.3,0.1

Type RM Length L Ch R = 1 ,28231.48,248.397300,248.397300,248.397300
XS GIS Cut Line= 6
734237.964589981731118.883354865734061.731441041 731651.22024118
734000.592355108731776.156156641733928.471664925731884.964839548
733724.797834935732119.587508944733074.575586674732682.660046238
#Sta/Elev= 30
8999.066492.32769070.961484.68429133.575 468.4429164.881464.26679299.906458.1353
9446.807445.0736 9478.57445.74969523.888438.67459675.127 430.6139744.953421.1833
9768.552410.04799801.255400.73489867.828393.92179893.225384.78039931.985387.7423
9994.838377.6034 10035.9380.407610055.74389.5055 10126.6404.119810224.14413.6433
10261.03420.847710420.45471.384110486.35 503.66210574.76555.572810631.34593.9257
10697.56 631.49410805.01 679.19310943.16736.548910987.23751.946611000.97761.5806
#Mann= 3 , 0 , 0
8999.066  0.0439       08999.066  0.0439       011000.97  0.0439       0
#XS Ineff= 2 , 0
       0                               0
Bank Sta=8999.066,11000.97
Exp/Cntr=0.3,0.1

Type RM Length L Ch R = 1 ,27983.09,248.397200,248.397200,248.397200
XS GIS Cut Line= 6
 734118.12901001731001.144322572733840.821324267731534.013973217
733690.462844432731774.373017453733583.565793703731922.714286389
733348.174187596732180.760348811732909.612474954732567.919955728
#Sta/Elev= 30
8999.023471.47849028.253481.80219081.686482.32549104.071474.25429160.034469.0293
9193.611452.50549327.922432.55119532.116439.99189789.032439.85779812.805434.9493
9824.692427.10929874.986422.28619910.705391.44939932.653379.589210006.35370.2188
10018.91371.395910047.36389.0109 10063.9395.591810198.88406.921310252.97424.0022
10336.22440.497110378.38 452.60810481.64498.061510501.35511.528510526.21522.2763
10609.53576.527710689.48617.910310736.93634.110810901.21672.543811000.96720.8429
#Mann= 3 , 0 , 0
8999.023    0.12       08999.023    0.12       011000.96    0.12       0
#XS Ineff= 2 , 0
       0                               0
Bank Sta=8999.023,11000.96
Exp/Cntr=0.3,0.1