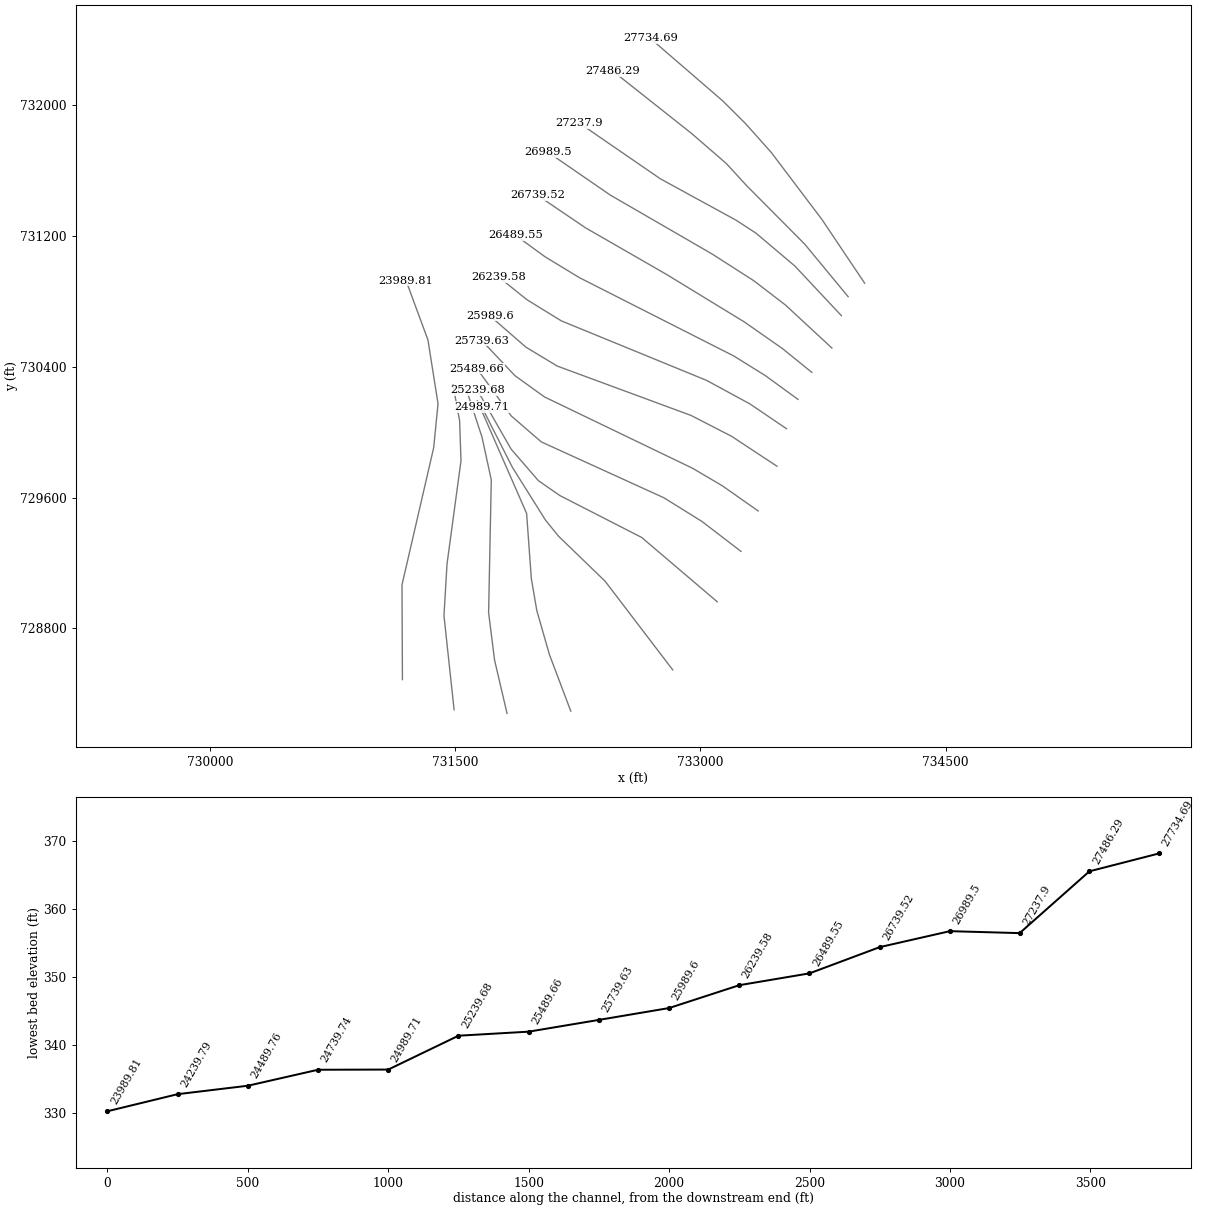
HEC-RAS study 4828_ras.prj: 4828

--- 4828_ras.g01 (geometry) --- (continued)

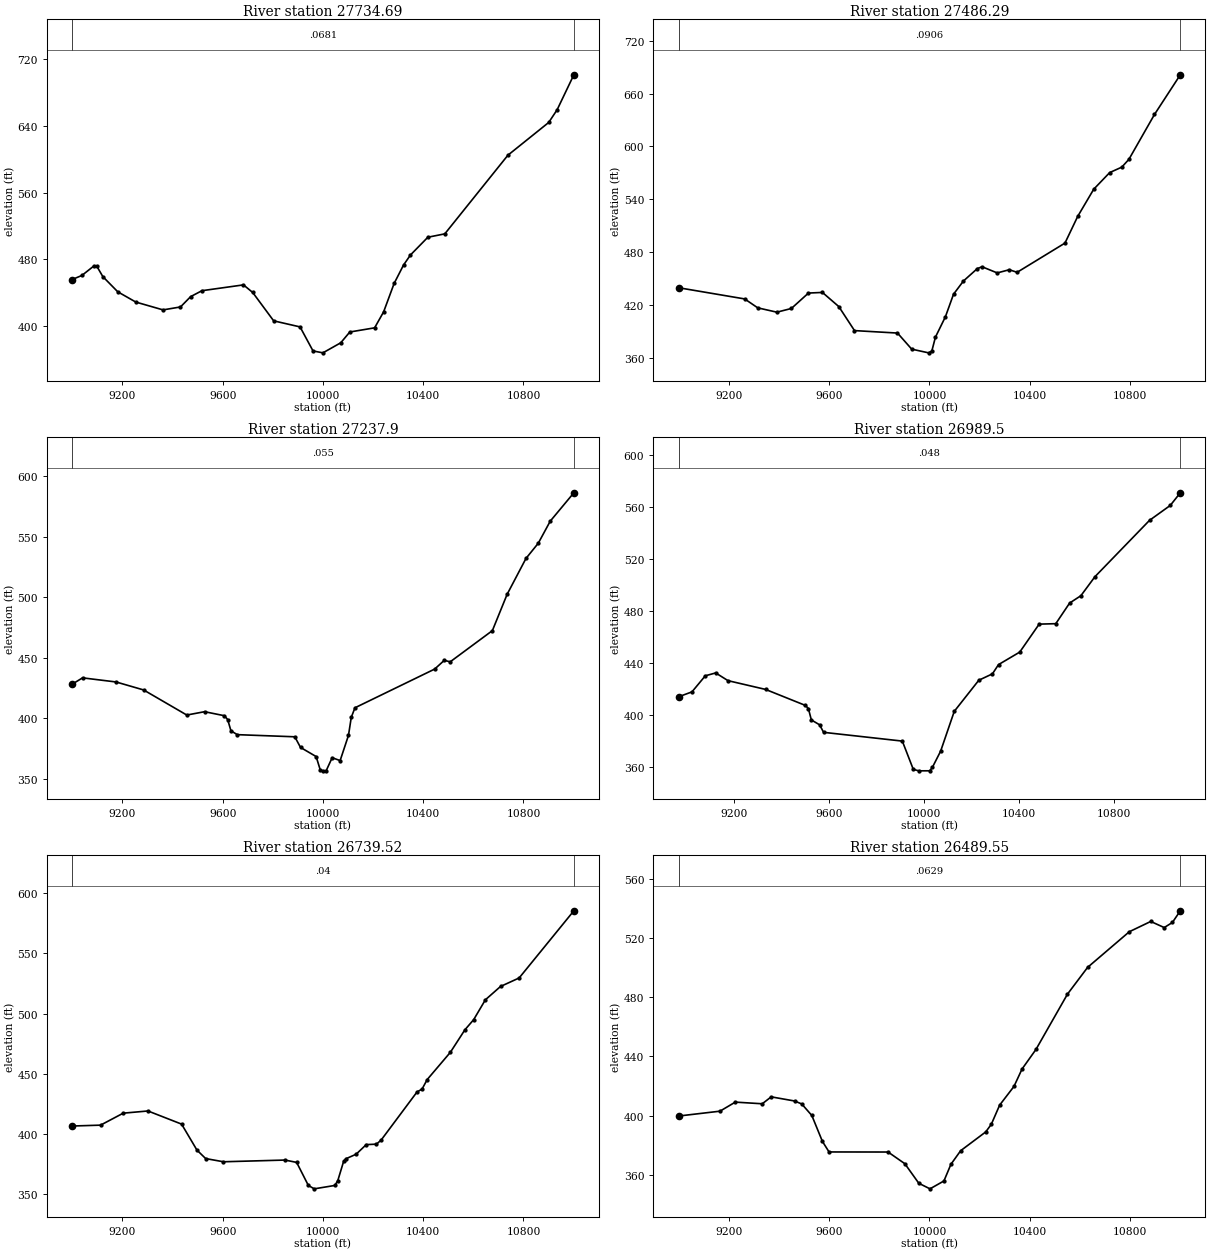
Type RM Length L Ch R = 1 ,27734.69,248.397200,248.397200,248.397200
XS GIS Cut Line= 6
734005.215282223730912.176380995733744.200941375731301.405076434
733433.296323822731712.666906786 733275.60770881731889.307499551
733137.842555159 732026.52941833732694.068620577732409.653644543
#Sta/Elev= 30
8999.015455.88259038.184460.80819085.917472.12439097.851471.77419121.717459.4394
9181.383 441.216 9253.31428.93739361.961419.55899431.533423.07519472.156435.4583
9517.306442.55199682.884449.51179719.752440.40499803.303406.44029908.579399.1861
9960.354370.38829999.832368.124710070.98380.168510107.11393.083410206.06398.0738
10242.04417.229310283.87451.201810321.32473.216410349.11 485.32910418.48506.5744
10486.08510.620610738.01604.857610900.75644.060110934.32659.274111000.98701.1359
#Mann= 3 , 0 , 0
8999.015  0.0681       08999.015  0.0681       011000.98  0.0681       0
#XS Ineff= 2 , 0
       0                               0
Bank Sta=8999.015,11000.98
Exp/Cntr=0.3,0.1

Type RM Length L Ch R = 1 ,27486.29,248.397200,248.397200,248.397200
XS GIS Cut Line= 6
733904.412413964730829.305097149733638.283524583731151.310212523
733283.738766251 731508.18282315733159.025649928731644.189945784
732946.984667838731827.649691863732464.216944387732209.959638861
#Sta/Elev= 30
8999.043 439.4549262.979426.71919315.018416.59859391.364411.67489449.192415.8792
9517.395433.3942  9573.1434.10859638.402 418.0449701.052390.75789872.599387.9574
9929.363369.6735 9996.55365.497810009.51367.491610023.96 383.33510063.77 406.482
10096.16432.091910135.61447.059910191.23461.226310209.92463.258110270.46456.2723
10318.61 459.88810349.81456.948810540.74490.149910591.76520.583610655.54551.3616
10719.13570.216510767.45 576.41410795.86585.2884 10897.9636.264911000.95681.3051
#Mann= 3 , 0 , 0
8999.043  0.0906       08999.043  0.0906       011000.95  0.0906       0
#XS Ineff= 2 , 0
       0                               0
Bank Sta=8999.043,11000.95
Exp/Cntr=0.3,0.1

Type RM Length L Ch R = 1 , 27237.9,248.397200,248.397200,248.397200
XS GIS Cut Line= 6
733862.815521863730713.609027783733578.767835886 731016.71139752
733340.799558995731217.815164472733218.973883624731297.157200289
 732755.43980242731550.643227424732260.710496202731890.816146535
#Sta/Elev= 30
8999.069427.98459040.898 433.2779174.651429.87239284.543423.2748 9456.73402.5437
9527.727405.30499606.916 401.9799619.913398.77599632.911389.51849658.183386.3345
9887.697384.57079910.409375.79619972.782  368.239989.903356.7515 10001.3 356.434
10012.73356.495910036.71367.294610068.53364.899510101.85385.778810112.96400.6423
10127.65408.538810445.68440.532710483.97447.742410507.69446.530610675.89472.3026
10734.68502.284810809.95531.960410859.17544.580810906.68562.755711000.97586.2225
#Mann= 3 , 0 , 0
8999.069   0.055       08999.069   0.055       011000.97   0.055       0
#XS Ineff= 2 , 0
       0                               0
Bank Sta=8999.069,11000.97
Exp/Cntr=0.3,0.1

Type RM Length L Ch R = 1 , 26989.5,249.973700,249.973700,249.973700
XS GIS Cut Line= 6
 733804.85256792730515.552139139733519.834083408730779.408998445
733326.443465501730927.603669807 733070.89818871 731091.38644667
 732449.17118457731451.137693301732070.821368426731711.609859228
#Sta/Elev= 30
8967.574413.71379024.096417.50789080.381 429.895 9124.05432.09529176.083426.1368
9334.078419.41029502.173407.07349514.605404.63619527.037395.90879561.788392.1516
 9578.62386.36299910.258379.6213 9956.49357.83399979.607356.722110025.68356.7496
10037.17359.504110071.63371.871810129.06402.523410232.44426.468110289.88431.3977
 10315.4438.497510404.95 448.15210486.64469.658710556.65470.0126   10615485.8921
 10662.4491.538910721.57506.165610951.61549.577911038.93561.049411081.29570.7846
#Mann= 3 , 0 , 0
8967.574   0.048       08967.574   0.048       011081.29   0.048       0
#XS Ineff= 2 , 0
       0                               0
Bank Sta=8967.574,11081.29
Exp/Cntr=0.3,0.1

Type RM Length L Ch R = 1 ,26739.52,249.973700,249.973700,249.973700
XS GIS Cut Line= 6
733682.445986981730366.307513902733502.537580952730512.033134993
733268.544092628730675.496248474732793.432196106730965.644109999
 732298.44434167731250.388170032732002.915663259731450.657189281
#Sta/Elev= 30
8999.031406.54649112.645407.27599203.141417.22179301.827419.04959435.954408.1396
9497.272386.54889532.039379.52049602.793376.86219848.382378.28189895.018 376.338
9941.673357.21049965.219354.377910047.49357.198910059.22361.232110082.49377.2446
10091.74379.396610132.24383.114810172.75391.116110213.25391.478310231.98394.8567
10375.27434.844710395.52437.300410415.78445.128310508.25 467.76210566.42486.5067
10601.33494.908510647.94511.378810708.33522.452810782.68529.520111000.97585.3225
#Mann= 3 , 0 , 0
8999.031    0.04       08999.031    0.04       011000.97    0.04       0
#XS Ineff= 2 , 0
       0                               0
Bank Sta=8999.031,11000.97
Exp/Cntr=0.3,0.1

Type RM Length L Ch R = 1 ,26489.55,249.973700,249.973700,249.973700
XS GIS Cut Line= 6
 733597.87224891730201.147064402733397.921477639 730346.62008123
733204.511175811730466.982281748732261.094052373730945.563401195
732050.423967961731073.531274609731871.032079556731204.522643548
#Sta/Elev= 30
8999.032399.72739164.358403.00939225.473409.13229333.081408.01519368.764412.6916
9461.966 409.8949490.681407.88049530.836 400.0939572.984382.60979599.489375.4583
 9835.04375.40749901.928367.51229957.668354.288810002.29350.532110057.87355.8616
10085.81367.131810124.57376.296610224.62388.995910246.85394.1348 10280.2407.1245
10337.37419.759210369.53431.511710425.21444.775710550.83 482.127 10631.1500.1905
 10797.5524.278110883.01531.214810936.75527.090410969.37530.533911000.98538.4309
#Mann= 3 , 0 , 0
8999.032  0.0629       08999.032  0.0629       011000.98  0.0629       0
#XS Ineff= 2 , 0
       0                               0
Bank Sta=8999.032,11000.98
Exp/Cntr=0.3,0.1

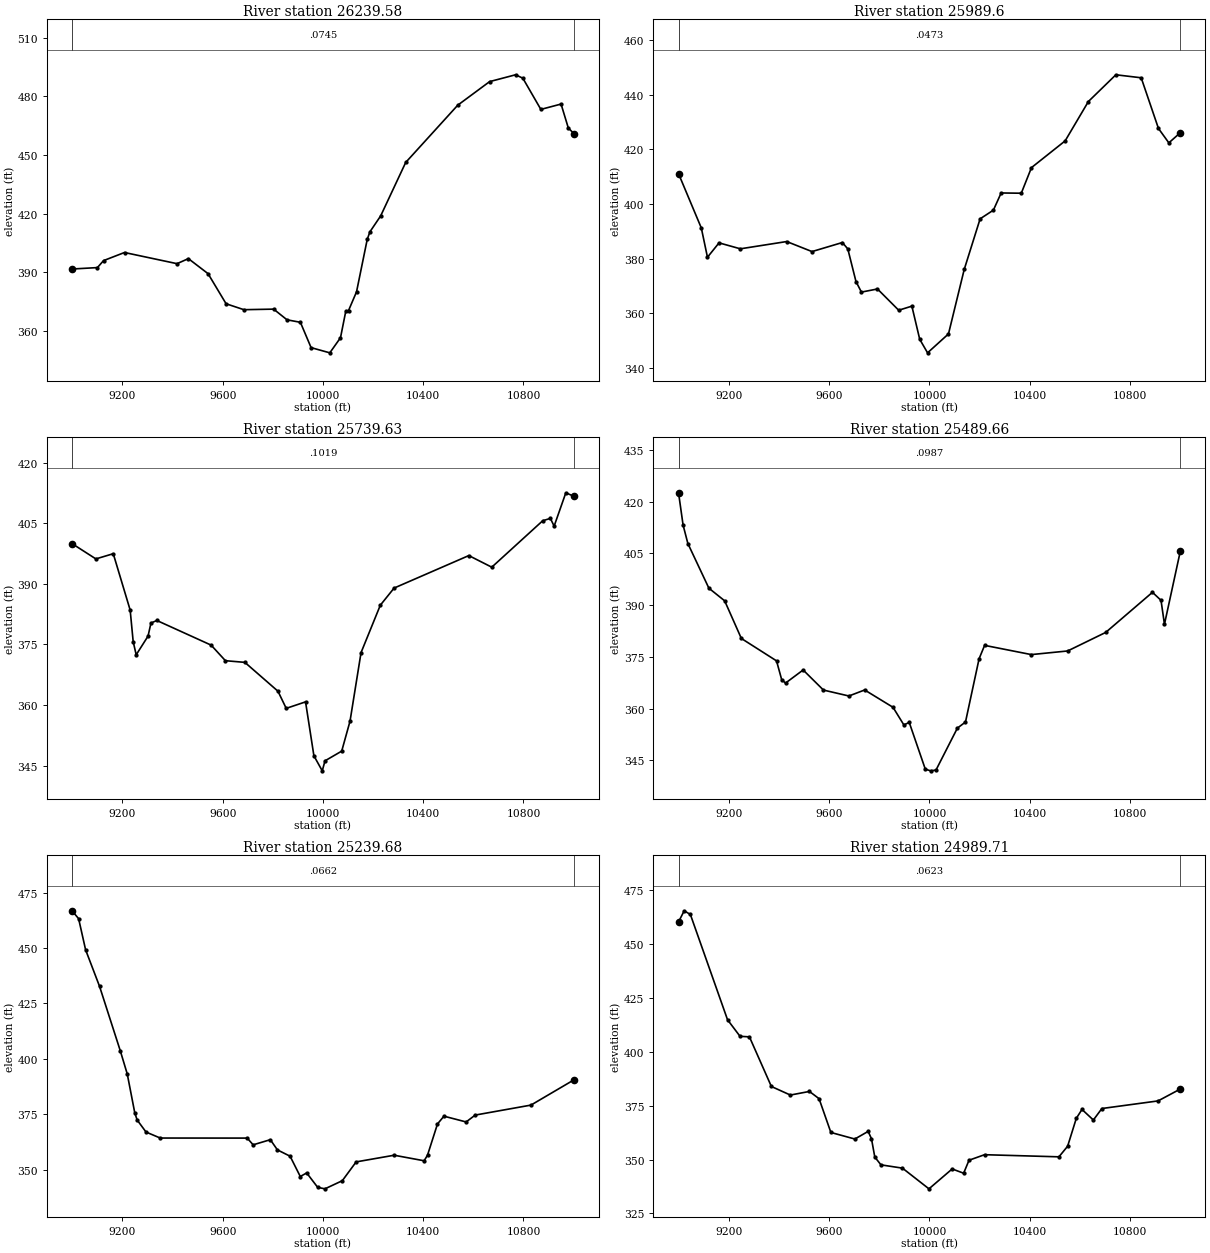
Type RM Length L Ch R = 1 ,26239.58,249.973700,249.973700,249.973700
XS GIS Cut Line= 6
733527.377112005730021.958338098733303.741859596730173.437738876
733038.831532913730317.334885468732149.799400428730681.619785371
731939.964126549730810.822193791731766.676759495730949.583409203
#Sta/Elev= 30
8999.055391.69869100.148 392.4239124.692396.00059208.232400.14649417.796 394.429
9463.074397.01729541.504389.32439613.556373.90669684.677370.87659803.242371.1647
9856.595365.69659909.948364.4321 9952.63 351.46410027.31348.797810069.95356.5303
10091.27370.253810101.93370.417310133.91380.007710176.55406.829410187.21410.7072
10230.19418.872710330.06446.229510537.79475.5462 10664.9487.604410768.48491.1006
10797.44489.341110869.27473.3819 10949.9476.116310978.88463.851311000.95461.0432
#Mann= 3 , 0 , 0
8999.055  0.0745       08999.055  0.0745       011000.95  0.0745       0
#XS Ineff= 2 , 0
       0                               0
Bank Sta=8999.055,11000.95
Exp/Cntr=0.3,0.1

Type RM Length L Ch R = 1 , 25989.6,249.973700,249.973700,249.973700
XS GIS Cut Line= 6
733469.149368978729792.348254979733191.037037333729975.705432884
 732943.68434556730103.012618455732125.378715681730404.872688818
731933.587467778730520.544258818731712.920087692730712.395044805
#Sta/Elev= 30
8999.055411.11659089.943 391.2139114.457380.48179160.628385.75459245.676383.5742
9430.572386.24019531.548382.56139652.634385.88029674.355383.53579706.937371.5863
9728.658367.7099 9792.72368.85299877.419361.06289929.935362.55989961.237350.4184
 9992.54345.445410076.02352.383110138.76375.999410202.21 394.565 10255.2397.7495
10286.09404.044310366.45403.952210407.07413.332510541.44423.137910634.18437.5671
 10743.8447.363510844.82446.263510913.75 427.67910955.14422.413111000.94426.1387
#Mann= 3 , 0 , 0
8999.055  0.0473       08999.055  0.0473       011000.94  0.0473       0
#XS Ineff= 2 , 0
       0                               0
Bank Sta=8999.055,11000.94
Exp/Cntr=0.3,0.1

Type RM Length L Ch R = 1 ,25739.63,249.973700,249.973700,249.973700
XS GIS Cut Line= 6
733354.214256693 729518.76730102733134.491081063729672.940376541
732953.315118956729779.665090711732047.144649129730216.184937491
731865.423647874730346.973983549 731664.93573254730559.810463378
#Sta/Elev= 30
8999.036399.94579094.021396.16389163.337 397.4529230.807383.5064 9242.84 375.692
9254.872372.43069302.081377.04469313.801380.28819337.242380.92439553.781374.8258
9610.779370.97089688.412370.55739820.389363.42219853.383359.17119930.536360.7799
9963.835347.43499997.134 343.70810008.24346.190410074.78348.589210107.94356.0031
 10151.9372.967410228.82384.704610283.77388.946110581.92  396.9910673.46394.1151
10876.66405.6072 10907.2406.197310922.27 404.28110968.95412.532611000.96411.6613
#Mann= 3 , 0 , 0
8999.036  0.1019       08999.036  0.1019       011000.96  0.1019       0
#XS Ineff= 2 , 0
       0                               0
Bank Sta=8999.036,11000.96
Exp/Cntr=0.3,0.1

Type RM Length L Ch R = 1 ,25489.66,249.973800,249.973800,249.973800
XS GIS Cut Line= 6
733249.059902302 729271.45405359733011.189540321729453.919353455
732777.456158848729599.470036978732027.445297614729941.211412938
731843.509688364730100.221995848731634.236922784730388.887871392
#Sta/Elev= 30
8999.071422.55259017.229413.20419036.282407.8529 9120.16394.90679183.117391.2443
 9249.67380.34259390.001373.85169410.547 368.4159425.848367.40759496.173 371.208
9577.167 365.3879678.721363.67149741.644365.41419854.724360.39349897.912355.3015
9919.506356.00269983.539342.464410004.84 341.98310026.17342.207610111.46354.3574
10143.89356.130110198.07 374.45210220.13378.339410406.54375.667110551.37376.7163
10703.24382.091110889.73393.711410923.91391.386910937.64384.461311000.94405.6453
#Mann= 3 , 0 , 0
8999.071  0.0987       08999.071  0.0987       011000.94  0.0987       0
#XS Ineff= 2 , 0
       0                               0
Bank Sta=8999.071,11000.94
Exp/Cntr=0.3,0.1

Type RM Length L Ch R = 1 ,25239.68,249.973700,249.973700,249.973700
XS GIS Cut Line= 6
733103.788497741728963.185544845732641.529892373729356.759814147
732141.004058131729613.006964241732009.421242641729704.479396447
731843.272053557729896.536596893731636.826325258730256.778078556
#Sta/Elev= 30
 8999.08466.79559025.234463.23149053.075449.18799108.758432.6955 9191.56  403.61
9219.226393.20259249.187375.68699258.711372.4359 9294.13367.00319350.777364.2993
9697.846 364.2769721.421361.23899789.999363.55659818.367358.9471  9868.8356.1069
9909.508346.95279935.074348.56129978.841342.076110007.79341.388610077.19  345.06
10132.36353.538510284.01356.546510403.52354.043210417.09356.5717 10456.9370.6582
10482.66374.159810571.13371.552110607.38374.655210829.74379.154411000.92390.5198
#Mann= 3 , 0 , 0
 8999.08  0.0662       0 8999.08  0.0662       011000.92  0.0662       0
#XS Ineff= 2 , 0
       0                               0
Bank Sta=8999.08,11000.92
Exp/Cntr=0.3,0.1

Type RM Length L Ch R = 1 ,24989.71,249.973700,249.973700,249.973700
XS GIS Cut Line= 6
 732831.40562556  728546.7332025 732418.09346657729088.763764432
732132.037210192729365.354838672732052.999751057 729463.18136623
 731851.24765193729784.507808363 731663.18756839730154.968570191
#Sta/Elev= 30
8999.056 460.1699021.621465.33289046.328463.61169194.568414.80369244.349407.1357
9281.881406.88169369.454383.8754 9445.14379.90419521.291381.5785 9559.66378.2233
 9606.81362.56159702.396359.51929755.482363.05559768.753359.64769782.025351.1625
9806.609347.54399892.399346.01699998.113336.423910090.68345.640510136.46343.6689
10157.94349.688110219.88352.250310516.63351.264910551.28356.176810585.92369.1065
 10608.6373.232910653.96 368.32710687.98 373.66210912.04 377.184 11000.9382.7002
#Mann= 3 , 0 , 0
8999.056  0.0623       08999.056  0.0623       0 11000.9  0.0623       0
#XS Ineff= 2 , 0
       0                               0
Bank Sta=8999.056,11000.9
Exp/Cntr=0.3,0.1

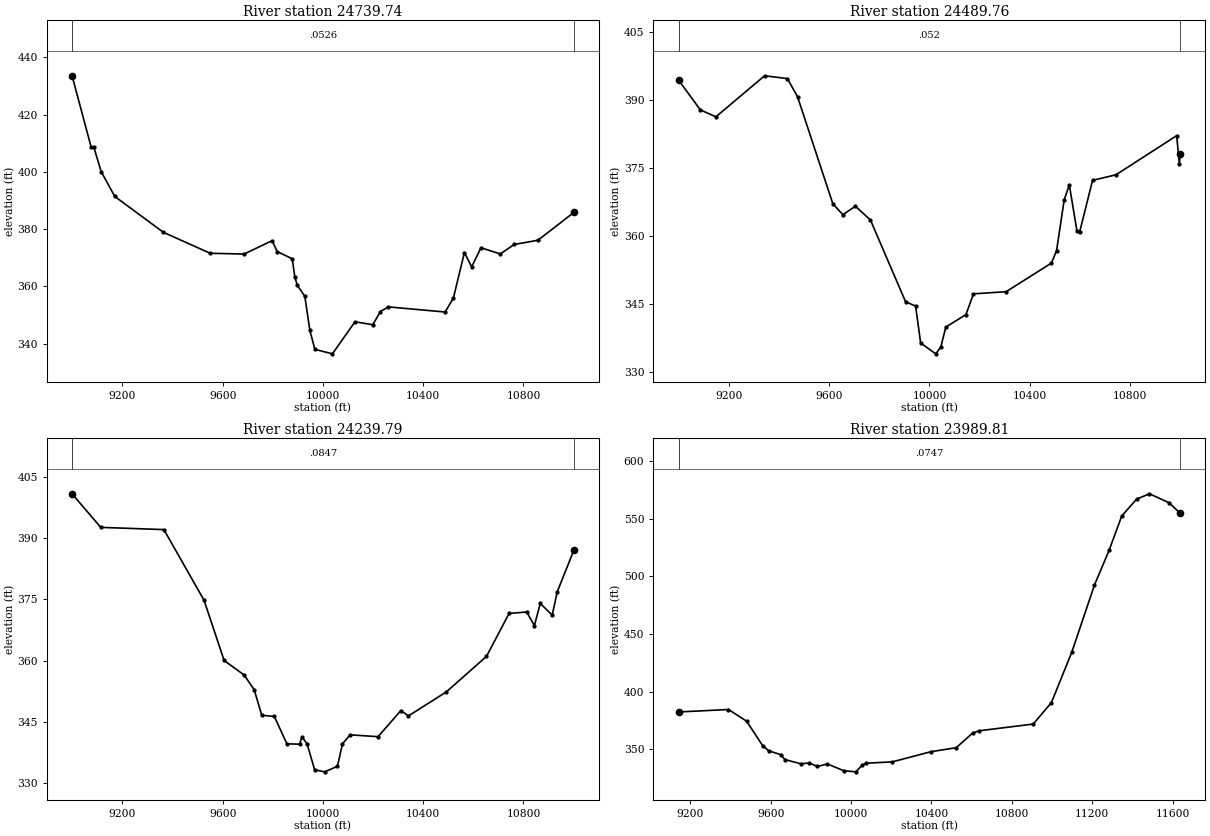
Type RM Length L Ch R = 1 ,24739.74,249.973700,249.973700,249.973700
XS GIS Cut Line= 6
 732207.91253075728294.328790679732076.839551033728641.305401893
732000.000054829728909.868070246731966.562625972729105.227561551
731937.692088725729503.742784162731636.491641791730192.468105563
#Sta/Elev= 30
8999.109433.59599075.171408.68299085.934408.60299115.162400.1244 9169.25391.4357
9363.381378.87679550.261 371.5539685.342371.27759797.071375.95649817.266372.1687
9877.619369.62319887.638363.26329897.658360.37559927.717 356.5089947.743344.5664
9967.744337.972310037.76336.397710127.84347.604210198.69 346.56510229.54351.1929
 10260.7352.8124 10487.2351.019210520.25355.873610564.32371.818510593.19 366.805
10630.43373.477710707.55371.314710762.64374.621410857.49376.094311000.92385.8215
#Mann= 3 , 0 , 0
8999.109  0.0526       08999.109  0.0526       011000.92  0.0526       0
#XS Ineff= 2 , 0
       0                               0
Bank Sta=8999.109,11000.92
Exp/Cntr=0.3,0.1

Type RM Length L Ch R = 1 ,24489.76,249.973700,249.973700,249.973700
XS GIS Cut Line= 6
731817.837077144728280.747135388731741.480386053728607.717089172
 731705.18170119728896.991418864731721.645209571729708.779227263
731664.803070929729970.506005233731573.767661451 730248.77606624
#Sta/Elev= 30
8999.066394.31949086.145387.75269148.157386.22689342.312395.25869433.378394.6423
9473.852390.64339614.588367.09589654.647364.68619704.683366.5407 9764.72363.5146
9904.807345.52169944.884344.56859964.936336.448810025.19334.053610045.28 335.536
10065.36339.943510145.71342.694610175.78347.261610305.88347.7293 10486.9354.0402
10507.17356.762510537.62367.930210558.07371.263110588.78360.995510599.11360.8453
10650.76372.237310744.21373.462610986.35382.080210996.94375.942311000.93378.1036
#Mann= 3 , 0 , 0
8999.066   0.052       08999.066   0.052       011000.93   0.052       0
#XS Ineff= 2 , 0
       0                               0
Bank Sta=8999.066,11000.93
Exp/Cntr=0.3,0.1

Type RM Length L Ch R = 1 ,24239.79,249.973700,249.973700,249.973700
XS GIS Cut Line= 6
731494.168677648728302.713811839731432.219384294728877.457374415
731450.814030121729194.525006003731536.218479763729824.919640698
731527.895799935730071.079346128731487.341130809730289.320251415
#Sta/Elev= 30
8999.038400.79659113.339392.5832 9365.43392.03889525.645374.75079605.661 360.043
  9685.7356.47879725.736352.89449755.809346.64499805.932346.35859856.168339.6598
 9906.43339.58189916.503341.35579936.648339.65639966.865333.298110007.17332.8164
10057.66334.170110077.89339.666110108.28341.861810219.68341.409310310.83347.7862
10341.22346.503810492.24352.3584 10652.4361.042310742.62371.543810813.12371.8934
10843.42368.557310867.02373.987710914.58371.132710934.94376.876811000.98387.0042
#Mann= 3 , 0 , 0
8999.038  0.0847       08999.038  0.0847       011000.98  0.0847       0
#XS Ineff= 2 , 0
       0                               0
Bank Sta=8999.038,11000.98
Exp/Cntr=0.3,0.1

Type RM Length L Ch R = 1 ,23989.81,299.972500,299.972500,299.972500
XS GIS Cut Line= 6
731178.091529369728487.260419285731175.434042156729066.851745471
731369.255834967729905.740825981731395.819963783730175.145889789
731334.061853439730565.367948294731200.590748936730926.660445541
#Sta/Elev= 30
9141.676 382.2979390.231 384.417 9480.26374.31269560.293353.01559590.347348.5811
9650.536345.22059670.645340.98719751.218337.2581 9791.63 338.0499832.043334.9843
9882.558337.10759963.623331.298610024.47330.312910055.11336.223310075.55337.7743
10205.82339.002710398.27347.832710523.02351.261410604.99363.963310635.51365.9159
10906.55371.806410996.97 390.47211098.29434.247911211.15492.534611283.83522.5975
 11346.7552.430411420.87567.0657 11484.8571.715111582.09563.924311638.23554.6789
#Mann= 3 , 0 , 0
9141.676  0.0747       09141.676  0.0747       011638.23  0.0747       0
#XS Ineff= 2 , 0
       0                               0
Bank Sta=9141.676,11638.23
Exp/Cntr=0.3,0.1