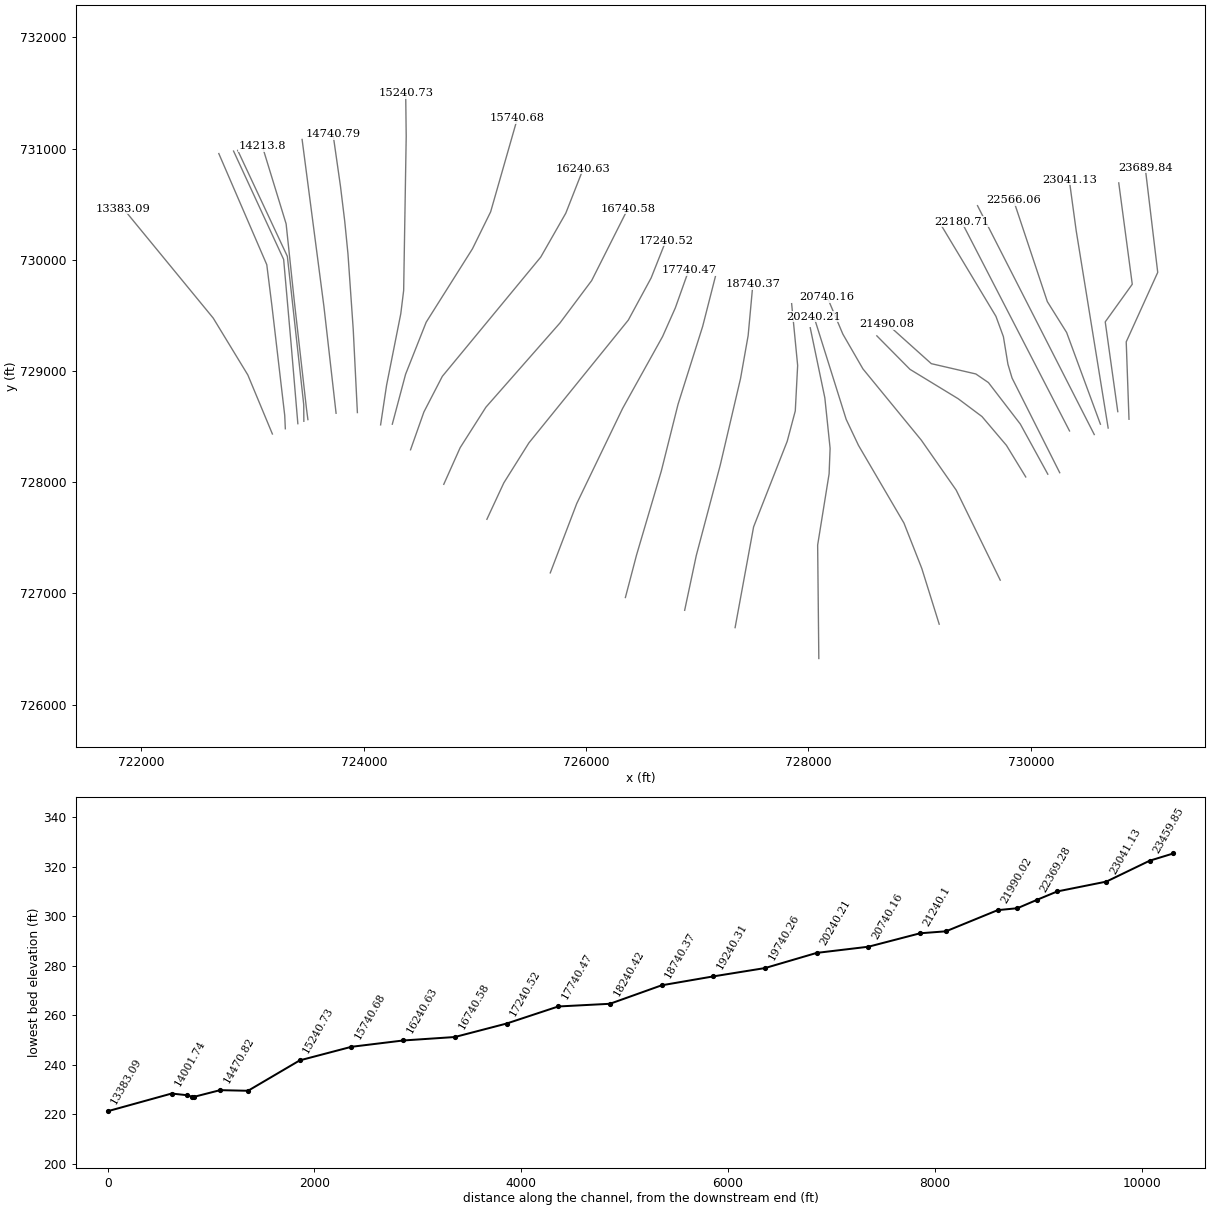
HEC-RAS study 4828_ras.prj: 4828

--- 4828_ras.g01 (geometry) --- (continued)

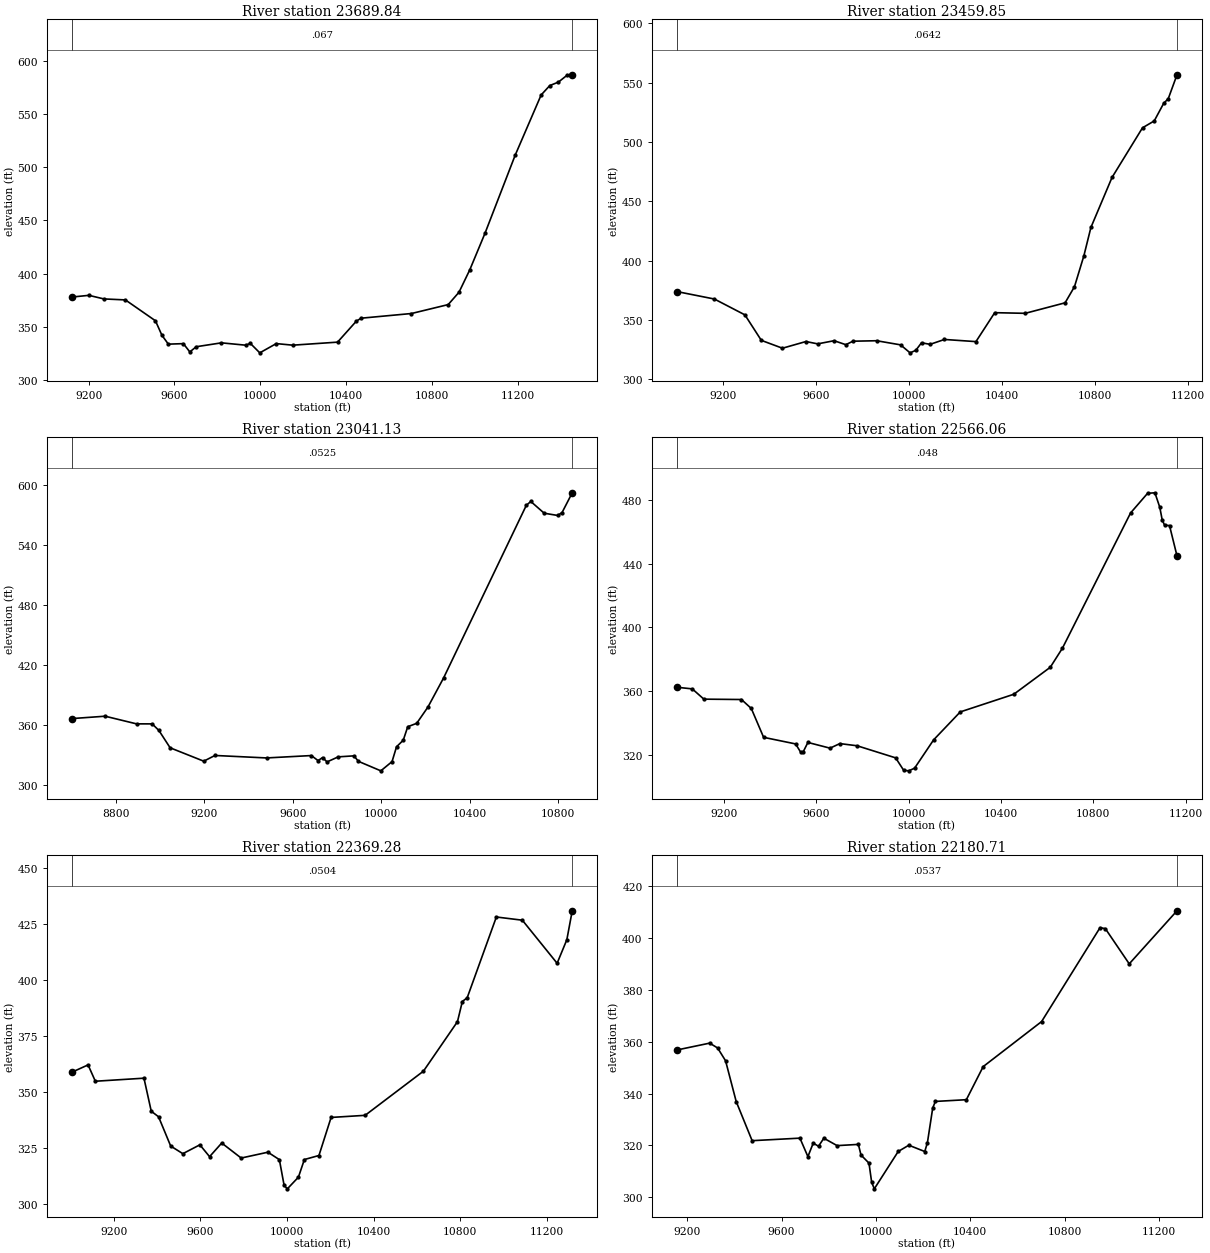
Type RM Length L Ch R = 1 ,23689.84,229.995700,229.995700,229.995700
XS GIS Cut Line= 4
730882.778156549728566.368379965730857.778156579729262.201713309
731141.111489922729887.201713309731028.611489892730828.868379965
#Sta/Elev= 30
9122.396377.87879201.078379.46889271.123 376.0989371.188 375.1749511.278355.5387
9541.297341.96369571.317333.57119641.362334.04599671.381326.26299701.401  331.14
9818.678334.79189931.546332.58949953.505 334.2559997.424325.391710074.28334.0836
10151.14332.599310359.75335.452410447.59355.252710469.55357.971310704.11362.3804
10875.32370.769510925.67382.402310976.03403.530911046.52437.726911187.52511.3394
11308.37567.931911348.66576.787411388.94580.041711429.23586.504311453.26586.9267
#Mann= 3 , 0 , 0
9122.396   0.067       09122.396   0.067       011453.26   0.067       0
#XS Ineff= 2 , 0
       0                               0
Bank Sta=9122.396,11453.26
Exp/Cntr=0.3,0.1

Type RM Length L Ch R = 1 ,23459.85,418.716200,418.716200,418.716200
XS GIS Cut Line= 4
730781.852230608728634.771157742730669.005008399729442.062824443
730912.060563952  729780.6044911 730790.53278622730692.062824413
#Sta/Elev= 30
9000.176374.05029161.963367.74919293.227354.41439363.907332.94369454.783326.3308
9555.755331.95979606.241329.99769676.921332.64449727.408329.30049757.699332.2374
9859.889332.62969962.769329.156210003.59322.441110028.21324.552610052.83330.9206
10089.76329.594210151.38333.704710286.95331.888510367.66356.256210498.81355.7064
10670.31364.557610710.67378.113710751.02404.072310781.29427.969510872.08470.0873
11003.23511.900211053.68517.689611094.03 532.39211114.21536.5036 11151.6556.5461
#Mann= 3 , 0 , 0
9000.176  0.0642       09000.176  0.0642       0 11151.6  0.0642       0
#XS Ineff= 2 , 0
       0                               0
Bank Sta=9000.176,11151.6
Exp/Cntr=0.3,0.1

Type RM Length L Ch R = 1 ,23041.13,475.069000,475.069000,475.069000
XS GIS Cut Line= 3
730695.278156549728487.201713324730407.778156549730262.201713309
730345.278156549730720.535046652
#Sta/Elev= 30
8602.818366.23578752.542368.60858894.367360.96228965.279360.9269 8995.67354.3291
9046.321337.02769198.276323.64439248.928329.35729481.925 326.8849684.532329.2683
9714.923 324.2219735.184327.25769755.444322.91629806.096327.97069877.008328.9714
9897.269323.48779998.572313.990110049.22323.218410069.48338.046910099.88344.6162
10120.14358.095210160.66361.492410211.31377.717910282.22406.876710656.09579.4573
10676.27583.290610736.83 571.53710797.38569.310210817.57572.222410863.53591.9756
#Mann= 3 , 0 , 0
8602.818  0.0525       08602.818  0.0525       010863.53  0.0525       0
#XS Ineff= 2 , 0
       0                               0
Bank Sta=8602.818,10863.53
Exp/Cntr=0.3,0.1

Type RM Length L Ch R = 1 ,22566.06,196.782900,196.782900,196.782900
XS GIS Cut Line= 4
730625.602230608728521.923935533 730321.78278622729346.576713309
730148.171675086  729624.3544911729844.352230608730535.812824413
#Sta/Elev= 30
8995.562362.48819062.783361.45259113.009355.00819275.924 354.7769318.553349.1454
9371.838331.0425 9510.38326.90579531.694321.88899542.351321.65379563.665 327.833
9659.579324.24789702.207327.11129776.807325.75299943.803318.16019978.674310.3421
10000.41310.013510025.84311.670110108.39329.459110223.73346.990210455.63358.0749
10613.75375.013610666.45387.0139 10961.6471.862611035.38484.210211067.01484.5358
11088.09475.468311098.63467.509411109.17464.098911130.25463.988111162.73444.9289
#Mann= 3 , 0 , 0
8995.562   0.048       08995.562   0.048       011162.73   0.048       0
#XS Ineff= 2 , 0
       0                               0
Bank Sta=8995.562,11162.73
Exp/Cntr=0.3,0.1

Type RM Length L Ch R = 1 ,22369.28,188.567500,188.567500,188.567500
XS GIS Cut Line= 2
730570.278156549728428.868379965729520.278156549730487.201713309
#Sta/Elev= 30
9006.972358.75299081.211361.99669114.889354.69889339.409356.06189373.087341.2979
9406.765338.82339462.894325.72949519.024322.32499597.606326.2808 9642.51320.9911
 9698.64327.07969788.447320.37189911.933322.97959964.866319.65619986.872 308.137
10001.74306.608510052.89311.832110080.32319.704510147.68321.508510203.81338.5188
10360.97339.4587 10630.4359.205310787.56381.335210810.01390.331410832.46392.0069
10967.17428.0987 11087.2426.669511247.82 407.42111292.73 417.94311317.65  430.88
#Mann= 3 , 0 , 0
9006.972  0.0504       09006.972  0.0504       011317.65  0.0504       0
#XS Ineff= 2 , 0
       0                               0
Bank Sta=9006.972,11317.65
Exp/Cntr=0.3,0.1

Type RM Length L Ch R = 1 ,22180.71,190.685900,190.685900,190.685900
XS GIS Cut Line= 2
730347.824452877728461.160046637729375.602230608730344.840602204
#Sta/Elev= 30
9156.037356.77689295.399359.43029329.159357.5695 9362.92 352.6199407.933336.9041
9475.453321.80589678.015322.78639711.775315.65939734.282320.85599756.788319.6624
9779.295322.75489835.562319.89829925.589320.37419936.843316.26529970.603313.1485
9981.856305.8261 9993.11303.230710094.39317.6351 10139.4320.058110206.92 317.626
10218.18321.009810240.68334.408510251.94336.946910383.19337.6137 10454.5350.3743
10702.07367.751810949.65403.954710972.16 403.60511073.44390.014511275.82410.4833
#Mann= 3 , 0 , 0
9156.037  0.0537       09156.037  0.0537       011275.82  0.0537       0
#XS Ineff= 2 , 0
       09484.049                       0
Bank Sta=9156.037,11275.82
Exp/Cntr=0.3,0.1

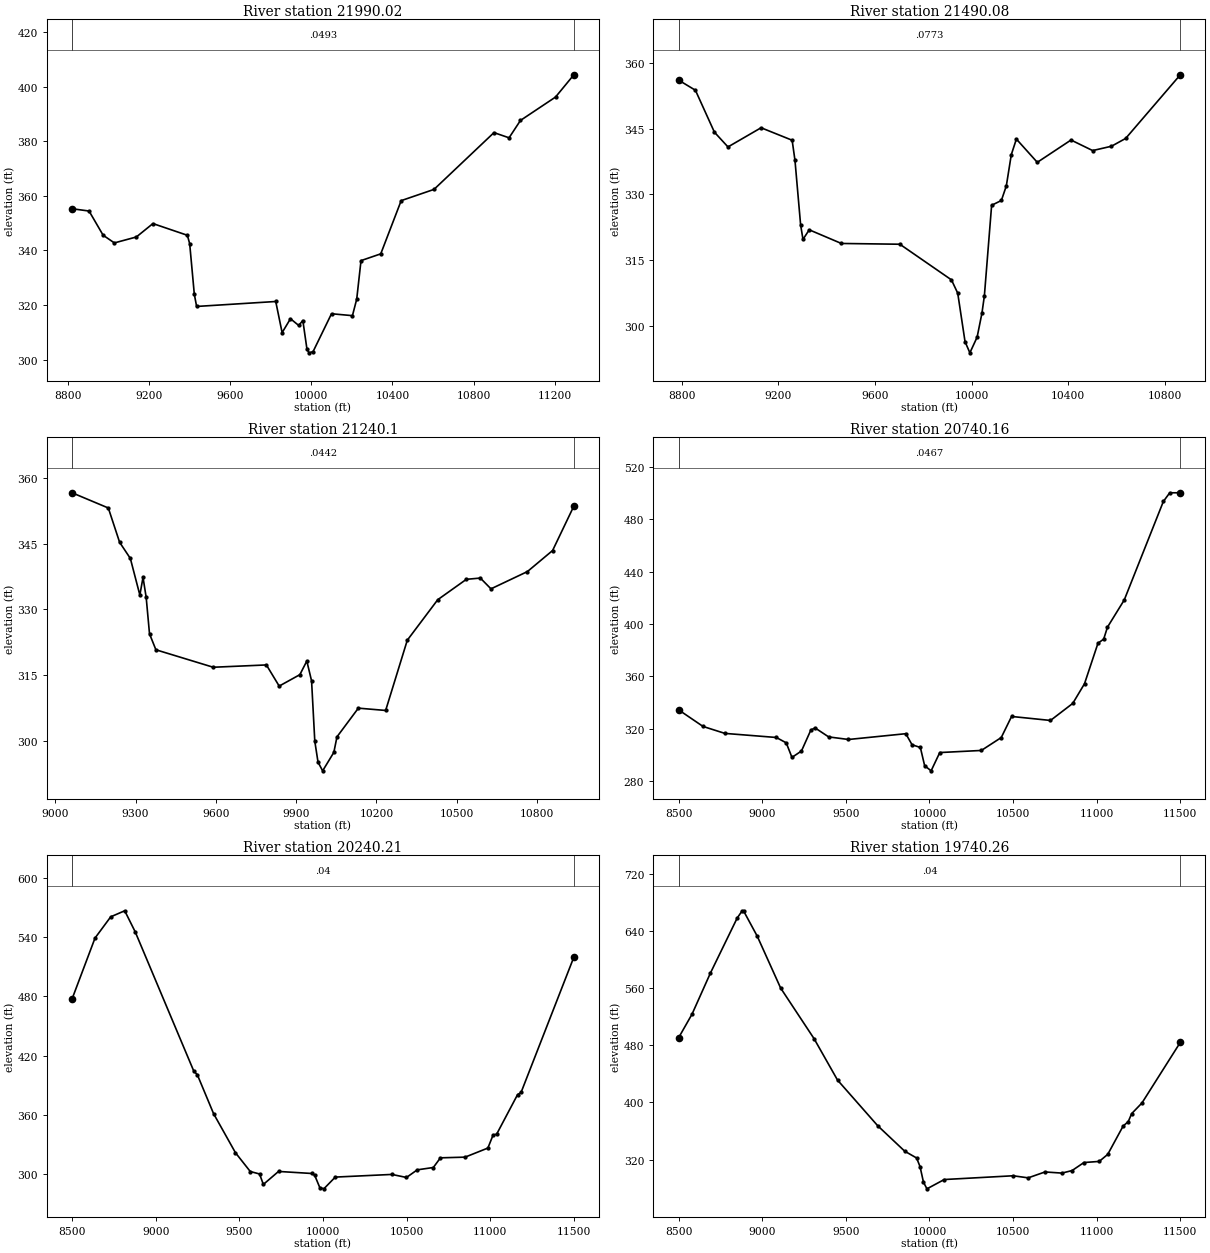
Type RM Length L Ch R = 1 ,21990.02,499.947400,499.947400,499.947400
XS GIS Cut Line= 6
730259.603154338728085.564754271729830.869114876728937.121471345
729793.810761273729061.328966245729753.094110012729309.064325616
729685.924415767729492.019384101729199.637113839730301.388350338
#Sta/Elev= 30
 8819.84355.23488903.627354.3958 8973.02345.5347 9028.38 342.719 9136.76344.8871
9218.579349.80219388.485345.51269399.888342.42039422.694323.92129434.097319.4455
9824.293321.25969855.713309.85649896.935314.94789937.636312.48029957.937314.2985
9978.099303.87659988.161302.453910008.29302.887510099.29316.772610202.55316.0733
10223.65322.130710244.78336.231610342.21338.7156 10442.9358.202610604.85362.3247
10900.48383.117310974.96381.219511031.21 387.58411204.05396.137911294.51404.3039
#Mann= 3 , 0 , 0
 8819.84  0.0493       0 8819.84  0.0493       011294.51  0.0493       0
#XS Ineff= 2 , 0
       09644.487                       0
Bank Sta=8819.84,11294.51
Exp/Cntr=0.3,0.1

Type RM Length L Ch R = 1 ,21490.08,249.973700,249.973700,249.973700
XS GIS Cut Line= 6
730152.552026066728072.183363237729905.344846129728522.813891307
729618.375035912728896.233175933729504.986972123728973.739485234
729104.780252755729066.252599552728708.405081958729421.882239178
#Sta/Elev= 30
8787.727356.06278857.608353.74418936.188344.18838992.316340.82379129.298345.1962
9257.818  342.359269.505337.77929292.879323.06339302.639319.75689328.573321.9362
9461.459318.82559703.541318.65029916.976310.52929942.988307.49479973.187 296.454
9993.201293.897310023.21297.470810043.22302.961810053.22 306.87110083.22327.5213
10123.61328.626410144.08331.949710164.62339.063210185.67342.616410272.22337.3147
 10411.7 342.401 10501.3339.997310579.13340.983610637.84342.763910864.04357.2703
#Mann= 3 , 0 , 0
8787.727  0.0773       08787.727  0.0773       010864.04  0.0773       0
#XS Ineff= 2 , 0
       09686.578                       0
Bank Sta=8787.727,10864.04
Exp/Cntr=0.3,0.1

Type RM Length L Ch R = 1 , 21240.1,499.947400,499.947400,499.947400
XS GIS Cut Line= 6
729953.994060844728047.363617584729780.400218278728331.458399177
729560.480282247728590.582058161729346.192760229728750.940251037
728912.740364313729015.213572606728614.730799437729316.498671383
#Sta/Elev= 30
9062.844356.58619198.283353.11349240.468345.28489280.625 341.5899316.112333.2314
9327.942337.27299339.771332.6913 9352.18324.3846 9376.03320.74119590.227316.7523
9788.873 317.2819836.666312.45159913.918 315.061 9939.91318.17489957.672313.6396
9969.722299.84839981.773295.0831    9999 293.10210040.86297.317810052.55300.8615
10132.41307.414710234.42306.8879 10315.3322.928110429.03332.172410535.99336.8263
10588.22337.114110627.93334.652510764.05 338.59510858.17343.4055 10937.6353.5474
#Mann= 3 , 0 , 0
9062.844  0.0442       09062.844  0.0442       0 10937.6  0.0442       0
#XS Ineff= 2 , 0
       09723.346                       0
Bank Sta=9062.844,10937.6
Exp/Cntr=0.3,0.1

Type RM Length L Ch R = 1 ,20740.16,499.947400,499.947400,499.947400
XS GIS Cut Line= 6
729724.595851336727119.247803038729328.467220634727929.014248017
729014.668945324728378.376569225 728489.63193163 729019.26196652
728309.249402811   729331.646065728168.715491359729664.122688405
#Sta/Elev= 30
8499.042334.32698645.574321.59628776.282316.2885 9084.05313.16269143.415309.0609
9177.527297.9359 9234.43302.81719290.586318.82899315.738320.48589397.046313.6051
9515.822311.63319858.682316.05619896.005307.60299945.768305.51769971.341291.5954
10010.02287.664710061.85301.640310310.56303.247410429.59 313.10610491.48329.2297
10724.23326.179110857.48339.216910927.71354.242611008.25385.189811042.51388.3686
11064.98397.462911165.63 418.31111399.42 493.54211437.66500.200211500.96500.2037
#Mann= 3 , 0 , 0
8499.042  0.0467       08499.042  0.0467       011500.96  0.0467       0
#XS Ineff= 2 , 0
       09826.479                       0
Bank Sta=8499.042,11500.96
Exp/Cntr=0.3,0.1

Type RM Length L Ch R = 1 ,20240.21,499.947400,499.947400,499.947400
XS GIS Cut Line= 6
 729175.56690196726723.348428987729018.859181512727225.306438938
728858.854080933727632.085493404728449.654512406728331.440444439
728339.076827673728565.060243032  728049.0777283729488.897572577
#Sta/Elev= 30
8499.062477.49888636.361539.19268730.221560.69758814.017566.8225 8877.09545.3721
9227.092404.46159248.449400.75689345.577361.33729476.533321.74469565.224302.7104
9620.713300.23379643.307289.62729734.147302.79449932.437300.73779949.842299.1563
9980.824286.516410005.08285.173210073.78297.074210412.31299.7701 10499.5296.6943
10564.17304.424710660.09306.782510702.73316.578810850.11317.277310986.58326.4818
11017.92 339.78711038.81340.483111164.16380.604711185.05382.793711500.92519.8882
#Mann= 3 , 0 , 0
8499.062    0.04       08499.062    0.04       011500.92    0.04       0
#XS Ineff= 2 , 0
       09806.396                       0
Bank Sta=8499.062,11500.92
Exp/Cntr=0.3,0.1

Type RM Length L Ch R = 1 ,19740.26,499.947500,499.947500,499.947500
XS GIS Cut Line= 6
728092.939855089726414.423750369728082.425979103727434.659361343
728185.448266155728075.292366492728194.428327015728304.799804539
728147.163047411728758.472101436728015.717572688729389.165428029
#Sta/Elev= 30
8499.074490.44158579.727523.60418689.831581.21598849.937658.24968879.944668.4267
8889.946667.44548969.963632.81829109.987560.17769309.991489.2764 9450.07431.3863
9690.568367.40329851.962331.79169923.296322.23139943.769 310.1939964.373288.3475
9985.075279.0383 10088.6292.074110500.45297.333410590.76294.4282 10691.4302.6852
10792.32301.084910853.07304.595210924.22315.863611015.73 317.44411066.69327.2995
11158.64366.924711189.36373.154111209.85384.3689 11271.3399.259111500.91484.1805
#Mann= 3 , 0 , 0
8499.074    0.04       08499.074    0.04       011500.91    0.04       0
#XS Ineff= 2 , 0
       09738.265                       0
Bank Sta=8499.074,11500.91
Exp/Cntr=0.3,0.1

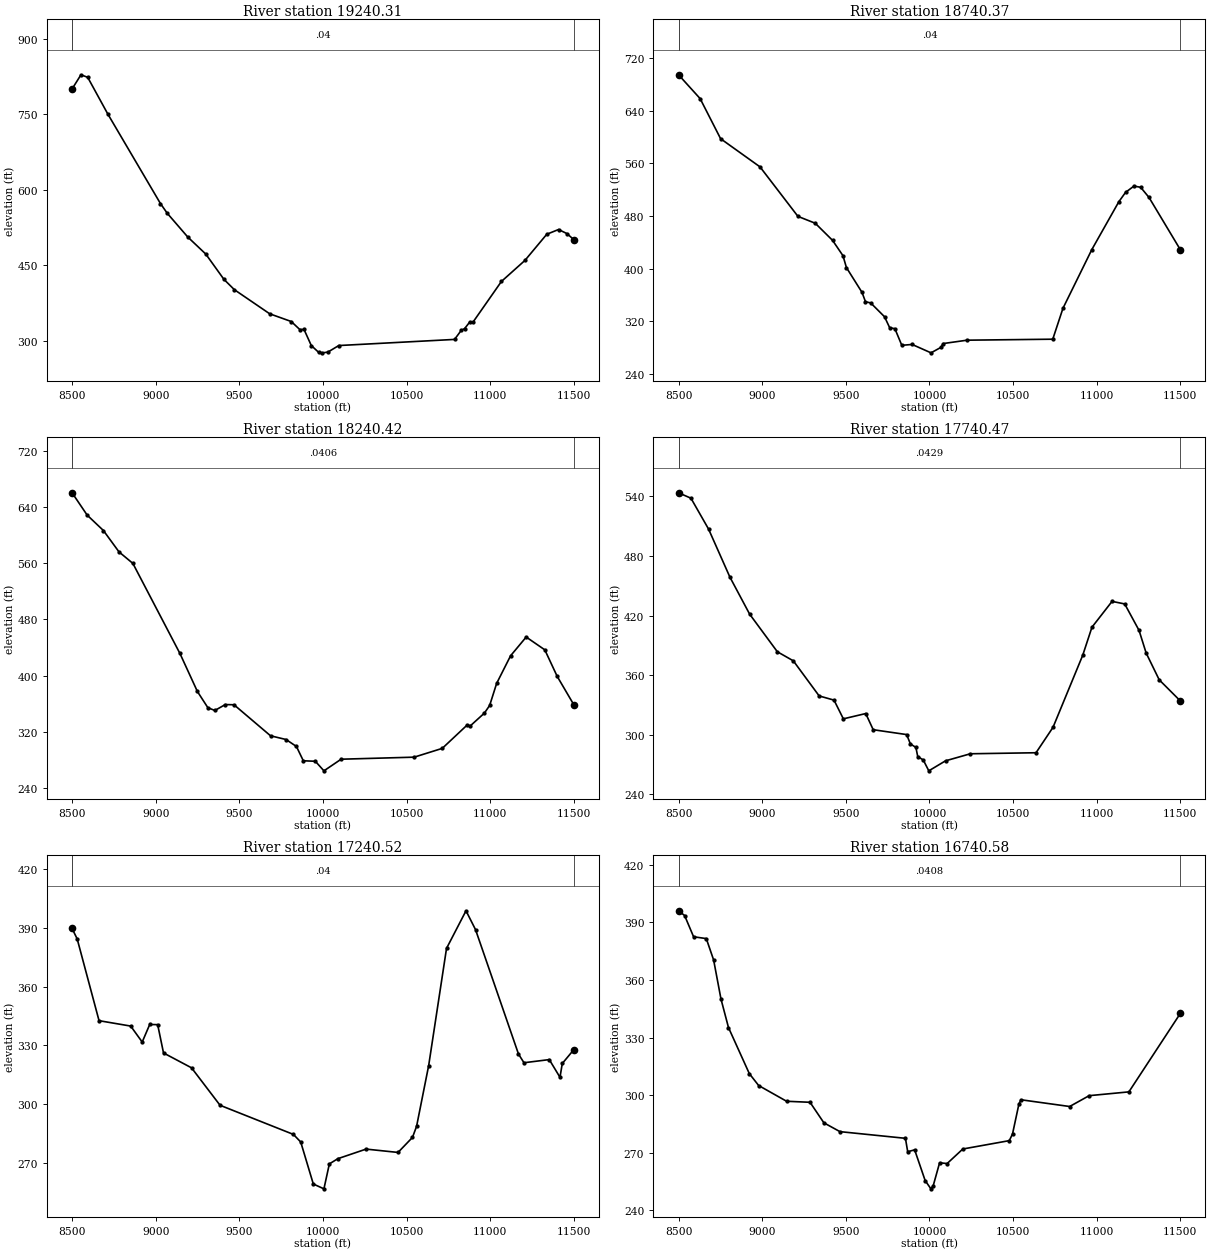
Type RM Length L Ch R = 1 ,19240.31,499.947400,499.947400,499.947400
XS GIS Cut Line= 6
727339.947758007726692.139879604727506.372138914727598.307962426
727808.522135123728367.692817897727881.247278077728641.233875066
727902.540126888729049.909664234 727848.52253369729605.876078626
#Sta/Elev= 30
8499.045800.23538552.276828.49598592.557823.44238713.525 750.0599027.672572.5266
9068.462553.15579191.055505.96719298.864472.08779407.629421.72929470.126401.2095
9681.215353.32039810.212337.96599862.594321.63329886.341322.42769930.216290.1688
 9974.09276.68749996.028 275.67210028.89277.053410094.62290.178810787.24 302.349
10827.24320.355510847.25323.777910877.25 336.61110897.26336.5686 11067.5417.5514
11208.05459.351711338.89511.4278 11409.4520.877611459.77512.720511500.94500.6084
#Mann= 3 , 0 , 0
8499.045    0.04       08499.045    0.04       011500.94    0.04       0
#XS Ineff= 2 , 0
       0                               0
Bank Sta=8499.045,11500.94
Exp/Cntr=0.3,0.1

Type RM Length L Ch R = 1 ,18740.37,499.947400,499.947400,499.947400
XS GIS Cut Line= 6
726886.330621975 726848.15598308726991.088486399727342.017188708
727206.730270032 728155.19137547727388.851780864728932.768637195
727457.307545299729319.145918701 727499.80549198729781.701580373
#Sta/Elev= 30
8499.019694.27348628.241658.07488750.732 597.2038986.464554.42119213.312479.2834
9316.901468.83769420.549 442.8079482.738419.58249503.468401.48839596.751 363.847
9617.481349.65469648.575347.84599731.341326.87989762.351310.1243 9793.36308.7563
9834.706283.4936 9896.44284.7962 10009.5272.064710071.16280.700410081.43286.1433
10225.29291.274610737.84292.782210798.97339.775510971.41428.797711132.95501.4395
11173.19515.688511223.47525.265811263.67523.433111313.83507.942111500.98428.6962
#Mann= 3 , 0 , 0
8499.019    0.04       08499.019    0.04       011500.98    0.04       0
#XS Ineff= 2 , 0
       0                               0
Bank Sta=8499.019,11500.98
Exp/Cntr=0.3,0.1

Type RM Length L Ch R = 1 ,18240.42,499.947400,499.947400,499.947400
XS GIS Cut Line= 6
726353.251874459726963.048946804726452.877535718 727342.81735705
726676.599186829  728101.5188941726826.883522706728701.148835389
727048.458756346729402.373780918727163.394286309729852.415801094
#Sta/Elev= 30
8499.023660.04568589.301628.29088686.572606.35398779.884575.95868862.828 559.596
9144.389 431.4739248.739 377.468 9311.35354.4264 9353.09350.44059415.701358.8581
9467.876358.56229686.277314.44729779.269309.13599841.263299.24179882.475278.8985
9954.415278.2084 10005.8264.5957 10108.6281.136310545.41284.0406 10713.7296.5487
10860.94329.3687 10881.9328.634810965.73346.708110997.17 357.56211039.07388.9806
11122.42428.226211215.78454.886111327.23436.670611401.28398.935211500.98358.5029
#Mann= 3 , 0 , 0
8499.023  0.0406       08499.023  0.0406       011500.98  0.0406       0
#XS Ineff= 2 , 0
       0                               0
Bank Sta=8499.023,11500.98
Exp/Cntr=0.3,0.1

Type RM Length L Ch R = 1 ,17740.47,499.947400,499.947400,499.947400
XS GIS Cut Line= 6
725677.547678738727184.423841415 725915.69446419727808.162222865
726328.034508809728663.390671103726687.597183919729309.869965611
 726802.42163516729568.030747956726923.681609123729908.723598716
#Sta/Elev= 30
8499.028543.69818573.223538.22628678.574507.1562 8806.32458.72198924.444421.3869
 9090.14383.50879185.713374.35779340.308 338.9819429.247334.75819485.057315.9033
9619.003 321.2419663.651304.94439863.888300.04689885.943290.66499919.025287.0937
9930.053277.89169963.135274.45379996.218 263.50710096.19273.593610244.82280.7082
 10637.7281.740910739.35307.366110917.29380.0525 10972.3408.249211092.53434.2606
11168.18431.689711254.08405.016611296.58 382.18211374.75355.203211500.96333.9629
#Mann= 3 , 0 , 0
8499.028  0.0429       08499.028  0.0429       011500.96  0.0429       0
#XS Ineff= 2 , 0
       0                               0
Bank Sta=8499.028,11500.96
Exp/Cntr=0.3,0.1

Type RM Length L Ch R = 1 ,17240.52,499.947400,499.947400,499.947400
XS GIS Cut Line= 6
725107.588048731727666.709521299 725259.71750422727993.879509535
725485.662711595728354.112765534726379.502590175729458.203377506
726584.926505493 729837.48737753726718.141087653730173.230800979
#Sta/Elev= 30
8499.048389.82568529.711384.45618660.432342.63658849.746339.87788918.623 331.707
 8963.53340.68619011.134340.61049046.131326.12129213.753318.51949384.331299.3588
9823.352284.43939866.968280.56139942.248259.077210005.78256.599610038.26269.3647
10089.35272.041410258.03276.932910449.12275.224510535.56282.925710560.05 288.579
 10632.4319.6774 10739.2379.624410855.72398.869710912.82389.200211169.67325.5783
11202.45321.115711353.94322.725911417.97313.662311431.73320.729811500.97 327.841
#Mann= 3 , 0 , 0
8499.048    0.04       08499.048    0.04       011500.97    0.04       0
#XS Ineff= 2 , 0
       09822.054                       0
Bank Sta=8499.048,11500.97
Exp/Cntr=0.3,0.1

Type RM Length L Ch R = 1 ,16740.58,499.947500,499.947500,499.947500
XS GIS Cut Line= 6
724719.694120022727981.203299042724867.063534317728310.576399671
725098.559177361728674.536141719725764.425817896729431.843989492
726049.877457638729813.552731091726374.609859434730457.984880253
#Sta/Elev= 30
8499.059 396.0248535.382393.5575 8589.12382.48038665.144381.53558709.027370.3798
8753.053 350.0198797.878335.18398922.467311.19688978.218304.99689145.506296.7844
9285.711296.25249368.599 285.5529464.801280.95959856.488277.4836 9869.97270.4967
9911.608271.47089974.336255.491710008.92251.161110022.77252.822710060.89264.7343
10105.89264.338710199.71271.914410477.68276.270810496.98279.705310534.94295.1762
10547.33297.570910838.81294.055410955.62299.703111193.28301.678611500.96342.5436
#Mann= 3 , 0 , 0
8499.059  0.0408       08499.059  0.0408       011500.96  0.0408       0
#XS Ineff= 2 , 0
       09851.334                       0
Bank Sta=8499.059,11500.96
Exp/Cntr=0.3,0.1

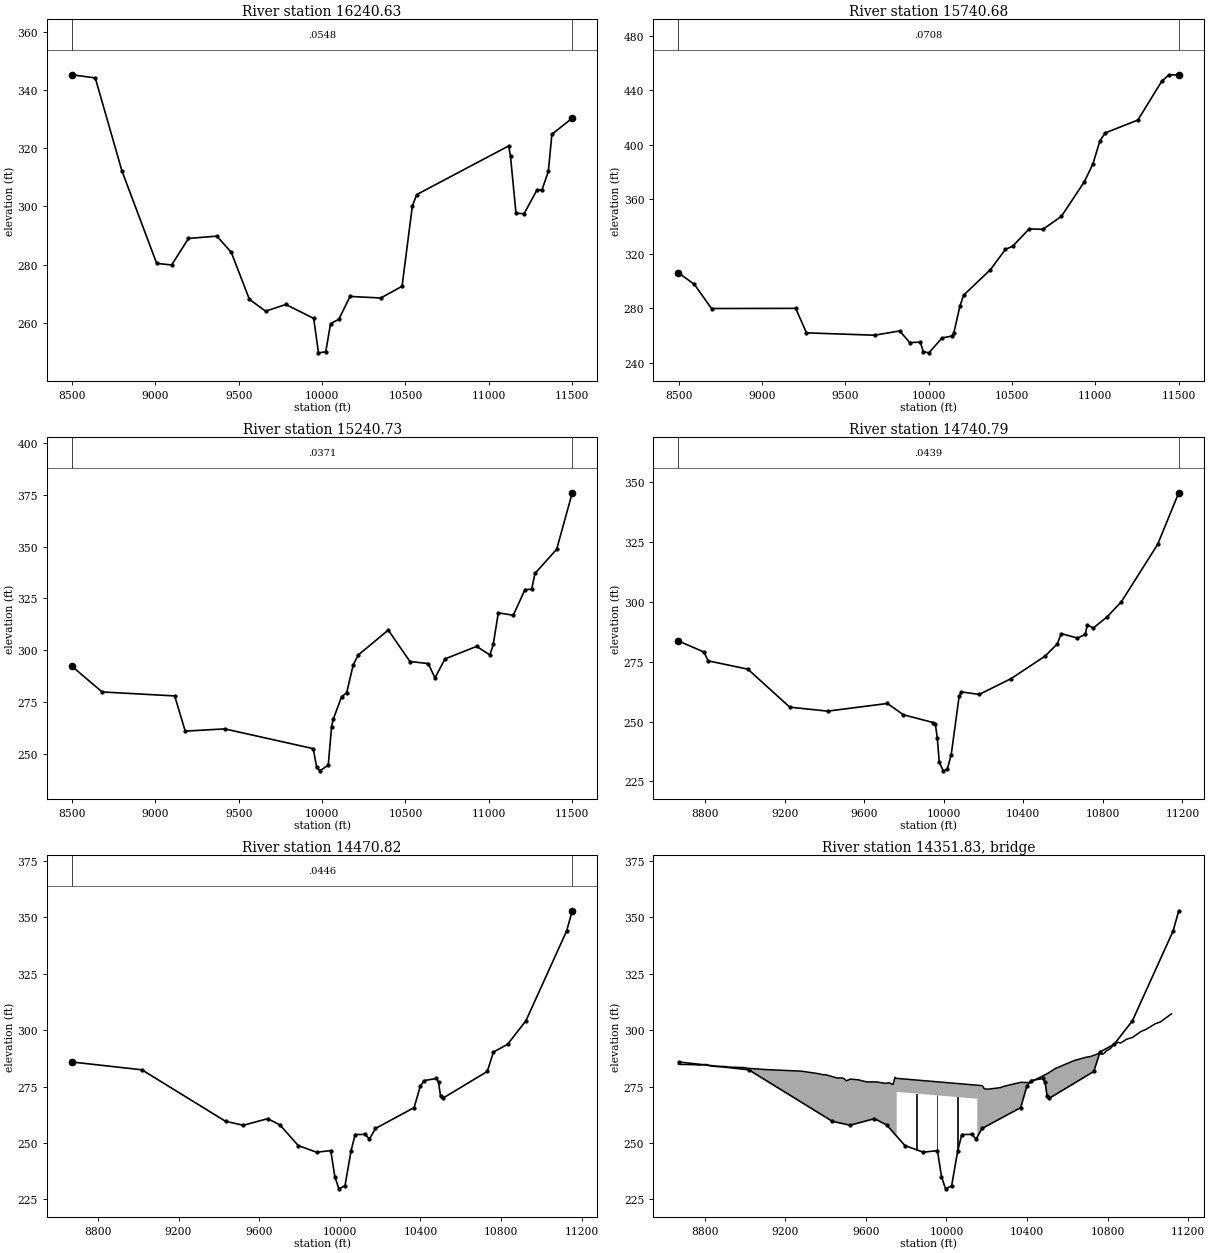
Type RM Length L Ch R = 1 ,16240.63,499.947400,499.947400,499.947400
XS GIS Cut Line= 6
724420.867398314728291.566349231724541.042150473728631.821604208
724706.744991786728952.242468824 725591.98514609730024.809334644
725817.215240262730419.574204188725974.831877272730820.929590231
#Sta/Elev= 30
8499.046345.16318638.715344.08198798.814 312.1599007.249280.44979097.106279.9041
9198.055289.01539368.311289.80199454.823284.25139563.423268.13329660.707  264.05
9782.257266.35629949.189261.58049978.159249.758610021.62 250.11110050.62259.7979
10100.02261.2494 10167.5269.116510351.89268.570610479.58272.591610541.43300.1678
 10567.6304.057911119.34320.751111130.33317.159411163.28297.6356   11212297.5139
11289.55305.676411319.38305.683911357.22311.994411378.55324.737811500.97330.2973
#Mann= 3 , 0 , 0
8499.046  0.0548       08499.046  0.0548       011500.97  0.0548       0
#XS Ineff= 2 , 0
       09728.737        10220.69       0
Bank Sta=8499.046,11500.97
Exp/Cntr=0.3,0.1

Type RM Length L Ch R = 1 ,15740.68,499.947400,499.947400,499.947400
XS GIS Cut Line= 6
724256.762368368 728521.79228656724376.095037771728970.559960391
724561.475562129729439.009884507 724977.64383214 730099.15433044
725141.110620582 730431.48858474725382.777084645731275.536780854
#Sta/Elev= 30
8499.042305.96648594.433297.45558697.351279.7318 9202.51279.84699267.219261.8821
9675.592260.13339826.621263.30199886.966254.71639949.747255.08819968.554248.0689
10001.72247.204510080.97258.147210139.14259.505310151.43261.904110188.01281.5241
10210.52289.578110371.13308.2766 10460.6323.112210504.85325.475310603.19338.1681
10686.11337.870410796.51347.356210933.58372.556710986.19385.945711027.91402.7947
11059.14408.599911255.43418.057411398.69 446.46711442.05 451.30811500.95451.1138
#Mann= 3 , 0 , 0
8499.042  0.0708       08499.042  0.0708       011500.95  0.0708       0
#XS Ineff= 2 , 0
       09345.388                       0
Bank Sta=8499.042,11500.95
Exp/Cntr=0.3,0.1

Type RM Length L Ch R = 1 ,15240.73,499.947400,499.947400,499.947400
XS GIS Cut Line= 6
724151.610903755728515.780145946724205.412752344728872.794333808
724333.185521009729516.079945265724358.926300579729724.791322323
724381.865738119731110.195872576724377.164807235731498.772932561
#Sta/Elev= 30
 8499.05292.15758679.921279.80499115.122277.89129178.566260.89169415.904 261.968
9946.738252.43089966.744243.5371 9986.75241.716410036.77244.490910056.78263.0534
10066.78 266.61510116.81277.530610146.81279.329410186.81292.986510216.81297.6539
10396.86309.681310526.93294.504510636.98293.5066   10677286.556910737.04295.7517
10927.11301.814111007.12297.626711027.13302.935911057.13317.991511147.14  316.84
11217.14  329.2111257.14329.387411277.14337.028211407.17348.674511500.97375.9681
#Mann= 3 , 0 , 0
 8499.05  0.0371       0 8499.05  0.0371       011500.97  0.0371       0
#XS Ineff= 2 , 0
       09399.477        10323.61       0
Bank Sta=8499.05,11500.97
Exp/Cntr=0.3,0.1

Type RM Length L Ch R = 1 ,14740.79,269.964200,269.964200,269.964200
XS GIS Cut Line= 6
 723942.78385812728626.387023091723905.458530456 729373.44955039
723858.072377145730053.061819732723828.863907576730347.903061241
723790.791428179730660.596883982723723.728067384731130.099056785
#Sta/Elev= 30
8666.575283.63588795.326 278.9858815.347275.34469015.562271.86199225.829256.0092
9416.133254.34479716.968 257.547 9797.19252.82329947.534249.57239957.551249.0437
9967.567243.33979977.584233.04249997.616229.427610017.65230.007810037.69236.2035
10077.76260.684810087.78262.389510178.13261.303410338.95267.928110510.12277.3488
10570.56282.375510590.71286.704610672.34284.8368 10711.6286.347210721.69290.3293
10751.97289.032210822.62293.792310893.27300.024311075.13323.906111181.44345.4817
#Mann= 3 , 0 , 0
8666.575  0.0439       08666.575  0.0439       011181.44  0.0439       0
#XS Ineff= 2 , 0
       09599.297        10205.69       0
Bank Sta=8666.575,11181.44
Exp/Cntr=0.3,0.1

Type RM Length L Ch R = 1 ,14470.82,257.027200,257.027200,257.027200
XS GIS Cut Line= 3
723751.122006744728620.302519873723642.066351056729578.434352234
723445.485180981731082.882082126
#Sta/Elev= 30
8671.533 285.8749018.456282.40689433.062 259.6039521.486 257.8539642.473260.7607
9702.983257.99589793.748248.85119884.513 245.9099955.108246.61499975.278235.0937
9995.448229.6788 10025.7 231.04810055.96 246.62110076.13253.718110126.55253.8219
10146.72251.683810176.98256.427110368.59265.667910398.85275.088510419.02277.6616
10479.53278.574310489.61276.8171 10499.7270.818310509.78269.755810731.65   281.7
10761.91 290.279 10832.5293.728710923.27 304.16211124.97343.890811153.09352.8694
#Mann= 3 , 0 , 0
8671.533  0.0446       08671.533  0.0446       011153.09  0.0446       0
#XS Ineff= 2 , 0
       09712.163        10139.58       0
Bank Sta=8671.533,11153.09
Exp/Cntr=0.3,0.1

Type RM Length L Ch R = 3 ,14351.83,,,
BEGIN DESCRIPTION:
END DESCRIPTION:
Bridge Culvert--1,0,-1,-1, 0
Deck Dist Width WeirC Skew NumUp NumDn MinLoCord MaxHiCord MaxSubmerge Is_Ogee
78.513600,100.000000,2.6,0, 60, 60, , , 0.95, 0, 0,0,,
 8669.45 8757.01 8767.09 8807.40 8827.55 8857.79 8898.09 8918.25 8998.87 9008.95
 9099.64 9281.04 9371.73 9381.81 9401.96 9456.80 9482.58 9492.66 9502.74 9522.89
 9563.20 9603.51 9653.90 9694.21 9714.36 9734.52 9744.59 9746.81 9752.83 9752.83
10152.8310152.8310177.9210188.0010208.1510265.2810288.7710369.3910419.7810439.93
10500.4010540.7610631.7210692.3610712.5810763.1110773.2210783.3210793.4310813.65
10833.8610854.0710864.1810894.5010923.7210965.2510992.6511036.0011061.5811117.28
  284.81  284.66  284.49  284.80  284.14  283.85  283.91  283.62  283.38  283.13
  282.54  281.81  280.60  280.31  280.20  278.80  278.81  278.44  277.55  278.31
  277.97  277.06  277.05  276.41  276.66  275.93  279.13  278.68  278.63  278.63
  275.59  275.59  275.38  273.98  273.84  274.49  275.18  276.88  276.71  278.01
  280.70  282.99  286.44  287.98  288.24  289.88  289.25  289.79  290.76  291.81
  293.89  294.59  294.24  295.97  296.76  299.38  300.42  302.81  303.60  307.22
 -715.19 -715.34 -715.51 -715.20 -715.86 -716.15 -716.09 -716.38 -716.62 -716.87
 -717.46 -718.19 -719.40 -719.69 -719.80 -721.20 -721.19 -721.56 -722.45 -721.69
 -722.03 -722.94 -722.95 -723.59 -723.34 -724.07 -720.87 -721.32 -721.37  272.63
  269.59 -724.41 -724.62 -726.02 -726.16 -725.51 -724.82 -723.12 -723.29 -721.99
 -719.30 -717.01 -713.56 -712.02 -711.76 -710.12 -710.75 -710.21 -709.24 -708.19
 -706.11 -705.41 -705.76 -704.03 -703.24 -700.62 -699.58 -697.19 -696.40 -692.78
 8669.45 8767.09 8807.40 8827.55 8857.79 8898.09 8918.25 8998.87 9008.95 9099.64
 9281.04 9371.73 9381.81 9401.96 9456.80 9482.58 9492.66 9502.74 9522.89 9563.20
 9603.51 9653.90 9694.21 9714.36 9734.52 9744.59 9746.81 9794.99 9794.9910172.76
10177.9210188.0010194.9910194.9910208.1510265.2810288.7710369.3910419.7810439.93
10500.4010540.7610631.7210692.3610712.5810763.1110773.2210783.3210793.4310813.65
10833.8610854.0710864.1810894.5010923.7210965.2510992.6511036.0011061.5811117.28
  284.81  284.49  284.80  284.14  283.85  283.91  283.62  283.38  283.13  282.54
  281.81  280.60  280.31  280.20  278.80  278.81  278.44  277.55  278.31  277.97
  277.06  277.05  276.41  276.66  275.93  279.13  278.68  278.31  278.31  275.44
  275.38  273.98  273.93  273.93  273.84  274.49  275.18  276.88  276.71  278.01
  280.70  282.99  286.44  287.98  288.24  289.88  289.25  289.79  290.76  291.81
  293.89  294.59  294.24  295.97  296.76  299.38  300.42  302.81  303.60  307.22
 -715.19 -715.51 -715.20 -715.86 -716.15 -716.09 -716.38 -716.62 -716.87 -717.46
 -718.19 -719.40 -719.69 -719.80 -721.20 -721.19 -721.56 -722.45 -721.69 -722.03
 -722.94 -722.95 -723.59 -723.34 -724.07 -720.87 -721.32 -721.69  272.31  269.44
  269.38  267.98  267.93 -726.07 -726.16 -725.51 -724.82 -723.12 -723.29 -721.99
 -719.30 -717.01 -713.56 -712.02 -711.76 -710.12 -710.75 -710.21 -709.24 -708.19
 -706.11 -705.41 -705.76 -704.03 -703.24 -700.62 -699.58 -697.19 -696.40 -692.78
Pier Skew, UpSta & Num, DnSta & Num=  ,9851.96, 2 ,9894.12, 2 , 0 , 0 , 0 ,,
    3.50    3.50
 -722.12  277.88
    3.50    3.50
 -722.44  277.56
Pier Skew, UpSta & Num, DnSta & Num=  ,9952.83, 2 ,9994.99, 2 , 0 , 0 , 0 ,,
    3.50    3.50
 -722.89  277.11
    3.50    3.50
 -723.21  276.79
Pier Skew, UpSta & Num, DnSta & Num=  ,10053.71, 2 ,10095.87, 2 , 0 , 0 , 0 ,,
    3.50    3.50
 -723.66  276.34
    3.50    3.50
 -723.98  276.02
BR Coef=-1 , 0 , 0 ,, 0 ,,,0.8,0,1,0,
WSPro=,,,, 1 ,,,, 0 ,,,, 0 ,,,,-1 ,-1 ,-1 , 0 , 0 , 0 , 0 , 0
BC Design=,, 0 ,, 0 ,,,,,,

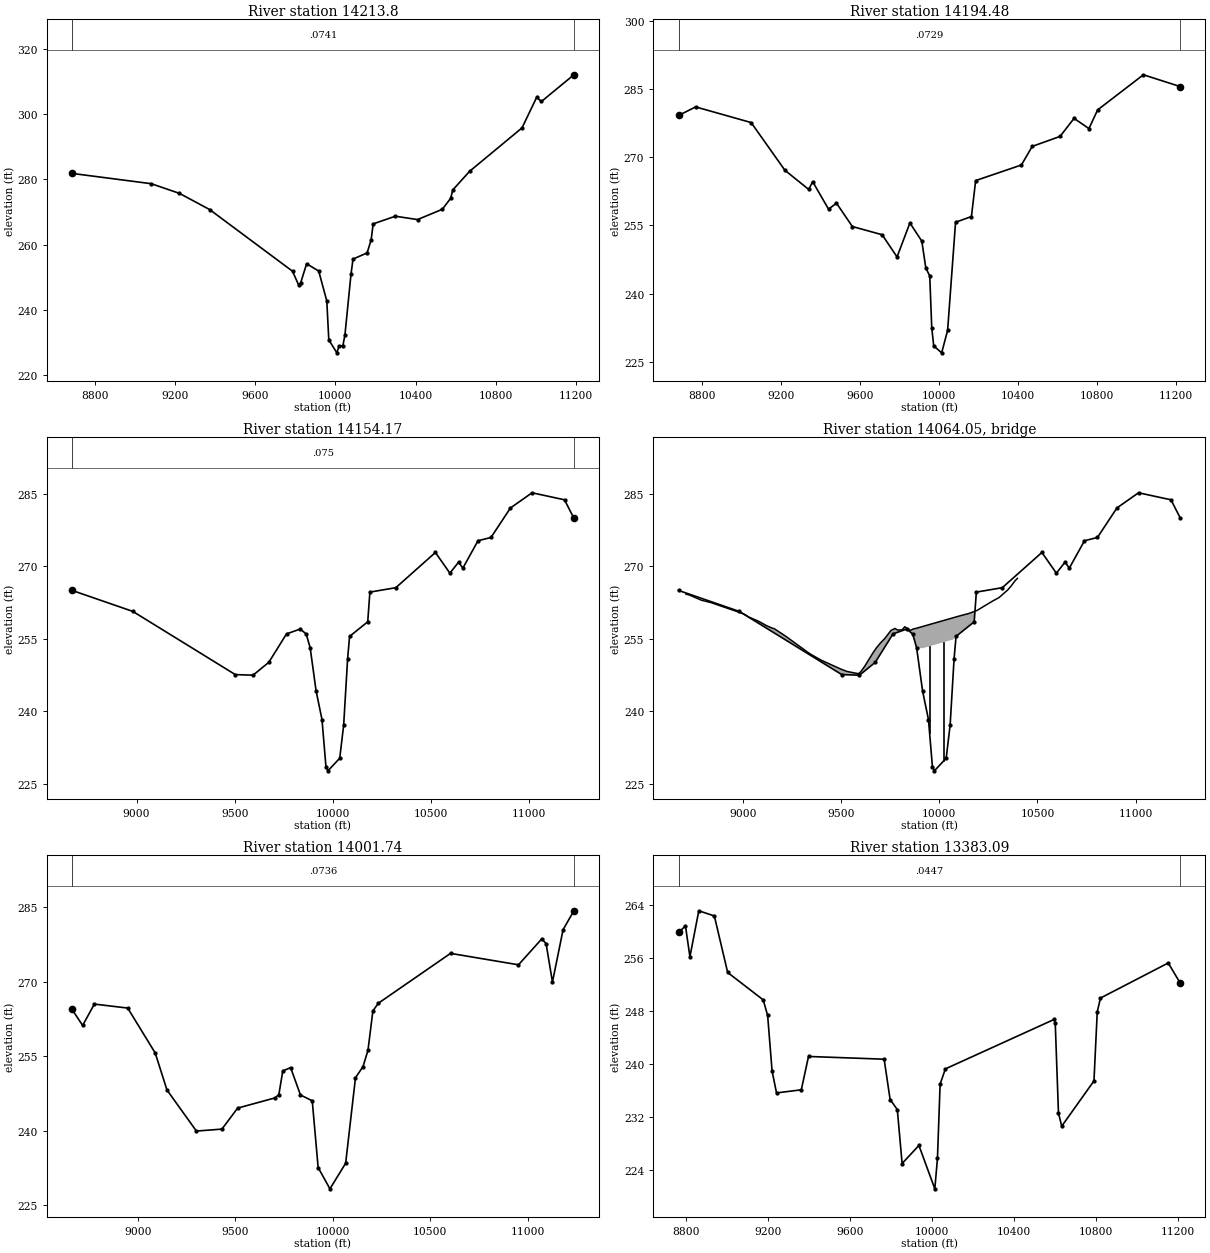
Type RM Length L Ch R = 1 , 14213.8,19.317500,19.317500,19.317500
XS GIS Cut Line= 5
723497.754811585728562.960932255723485.208712131  728658.7294911
723375.833712131729624.007268906723301.881712288730323.335963041
723087.604243407731022.150771513
#Sta/Elev= 30
8686.949281.81719081.702278.67119222.598275.70699373.558270.73819786.156251.8985
9816.323247.73919826.379248.23739856.546254.18969916.881251.94289957.104242.8033
 9967.16230.894110007.38226.931410017.44228.880710037.55229.154110047.61232.4355
10077.77250.941210087.83255.610210158.22257.497510178.33261.498610188.39266.3749
   10299268.722810409.61267.691210533.18270.846610575.01274.220210585.47276.7629
10669.15282.454510930.64295.744111003.86305.108511027.47303.815111189.15311.9887
#Mann= 3 , 0 , 0
8686.949  0.0741       08686.949  0.0741       011189.15  0.0741       0
#XS Ineff= 2 , 0
       09793.259        10172.73       0
Bank Sta=8686.949,11189.15
Exp/Cntr=0.3,0.1

Type RM Length L Ch R = 1 ,14194.48,40.304200,40.304200,40.304200
XS GIS Cut Line= 4
723461.185526103728548.168861717723460.121906579728698.139213324
 723312.89968437730031.472546637722866.503939838730984.630720002
#Sta/Elev= 30
8679.164279.15058765.997 281.0339047.317277.5938 9218.35267.12159339.079262.9095
9359.201264.62039439.687258.5724 9479.93259.89839560.417254.76289711.328 252.963
9786.972248.08899852.179 255.5549912.544251.55089932.665 245.7029952.787243.8853
9962.847232.54829972.908 228.54510013.15227.026610043.33231.971410083.58255.7006
10164.06256.956910185.51264.8557 10417.4268.279810472.14272.3553 10613.6274.5611
10684.34278.520810759.71276.271910803.88280.374711035.77288.089111223.09285.4927
#Mann= 3 , 0 , 0
8679.164  0.0729       08679.164  0.0729       011223.09  0.0729       0
#XS Ineff= 2 , 0
       09797.373        10175.84       0
Bank Sta=8679.164,11223.09
Exp/Cntr=0.3,0.1

Type RM Length L Ch R = 1 ,14154.17,152.431100,152.431100,152.431100
XS GIS Cut Line= 4
723407.305403411728526.374654785723346.233017683729248.139213309
723279.566351026730003.694768876722829.024731777730978.270611968
#Sta/Elev= 30
8671.484264.99238981.213260.64059503.104247.55559593.454247.43399673.765250.0946
9764.114255.98519834.386256.99699864.503255.94899884.581253.10329914.697 244.194
9944.814238.24379964.891228.5184 9974.93227.622510035.16230.237310055.24 237.119
10075.32250.835210085.36255.474310177.79258.485610188.81264.639210321.01265.5594
10522.66  272.8510596.43268.5645 10640.5270.834510662.53269.612210739.65275.2807
10805.75275.957410904.91282.066511015.07285.214611180.33283.7607   11228279.9573
#Mann= 3 , 0 , 0
8671.484   0.075       08671.484   0.075       0   11228   0.075       0
#XS Ineff= 2 , 0
       09807.154        10183.05       0
Bank Sta=8671.484,11228
Exp/Cntr=0.3,0.1

Type RM Length L Ch R = 3 ,14064.05,,,
BEGIN DESCRIPTION:
END DESCRIPTION:
Bridge Culvert--1,0,-1,-1, 0
Deck Dist Width WeirC Skew NumUp NumDn MinLoCord MaxHiCord MaxSubmerge Is_Ogee
51.281200,49.868700,2.6,0, 46, 46, , , 0.95, 0, 0,0,,
 8709.27 8724.99 8787.00 8837.32 8998.36 9018.49 9028.54 9078.57 9118.60 9148.62
 9158.62 9218.66 9328.74 9348.75 9398.86 9499.45 9529.63 9579.93 9589.95 9599.98
 9620.02 9660.12 9680.17 9702.89 9721.97 9753.81 9775.03 9786.58 9810.21 9824.46
 9833.85 9843.23 9857.48 9868.10 9879.72 9879.7210093.9510093.9510150.7910191.54
10273.4310304.1410349.4010365.2310385.4610397.80
  264.21  264.07  262.98  262.46  260.21  259.78  259.49  258.62  257.72  257.18
  257.08  255.47  252.21  251.68  250.53  248.68  248.21  247.80  247.78  248.16
  249.28  251.93  253.13  254.23  255.01  256.71  257.12  256.79  256.81  257.47
  257.19  256.75  256.80  257.02  257.11  257.11  259.60  259.60  260.22  260.83
  262.83  263.50  265.12  265.86  266.96  267.48
 -735.79 -735.93 -737.02 -737.54 -739.79 -740.22 -740.51 -741.38 -742.28 -742.82
 -742.92 -744.53 -747.79 -748.32 -749.47 -751.32 -751.79 -752.20 -752.22 -751.84
 -750.72 -748.07 -746.87 -745.77 -744.99 -743.29 -742.88 -743.21 -743.19 -742.53
 -742.81 -743.25 -743.20 -742.98 -742.89  252.61  255.10 -740.40 -739.78 -739.17
 -737.17 -736.50 -734.88 -734.14 -733.04 -732.52
 8709.27 8724.99 8787.00 8837.32 8998.36 9018.49 9028.54 9078.57 9118.60 9148.62
 9158.62 9218.66 9328.74 9348.75 9398.86 9499.45 9529.63 9579.93 9589.95 9599.98
 9620.02 9660.12 9680.17 9702.89 9721.97 9753.81 9775.03 9786.58 9810.21 9824.46
 9833.85 9843.23 9857.48 9868.10 9907.06 9907.0610121.3010121.3010171.0610191.54
10273.4310304.1410349.4010365.2310385.4610397.80
  264.21  264.07  262.98  262.46  260.21  259.78  259.49  258.62  257.72  257.18
  257.08  255.47  252.21  251.68  250.53  248.68  248.21  247.80  247.78  248.16
  249.28  251.93  253.13  254.23  255.01  256.71  257.12  256.79  256.81  257.47
  257.19  256.75  256.80  257.02  257.43  257.43  259.92  259.92  260.48  260.83
  262.83  263.50  265.12  265.86  266.96  267.48
 -735.79 -735.93 -737.02 -737.54 -739.79 -740.22 -740.51 -741.38 -742.28 -742.82
 -742.92 -744.53 -747.79 -748.32 -749.47 -751.32 -751.79 -752.20 -752.22 -751.84
 -750.72 -748.07 -746.87 -745.77 -744.99 -743.29 -742.88 -743.21 -743.19 -742.53
 -742.81 -743.25 -743.20 -742.98 -742.57  252.93  255.42 -740.08 -739.52 -739.17
 -737.17 -736.50 -734.88 -734.14 -733.04 -732.52
Pier Skew, UpSta & Num, DnSta & Num=  ,9950.46, 2 ,9977.81, 2 , 0 , 0 , 0 ,,
    4.00    4.00
 -742.07  257.93
    4.00    4.00
 -741.75  258.25
Pier Skew, UpSta & Num, DnSta & Num=  ,10023.21, 2 ,10050.55, 2 , 0 , 0 , 0 ,,
    4.00    4.00
 -741.22  258.78
    4.00    4.00
 -740.90  259.10
BR Coef=-1 , 0 , 0 ,, 0 ,,,0.8,0,1,0,
WSPro=,,,, 1 ,,,, 0 ,,,, 0 ,,,,-1 ,-1 ,-1 , 0 , 0 , 0 , 0 , 0
BC Design=,, 0 ,, 0 ,,,,,,

Type RM Length L Ch R = 1 ,14001.74,618.648200,618.648200,618.648200
XS GIS Cut Line= 5
723294.715387821728480.832626015723289.288573265728600.222546652
723174.705239922729581.472546652723127.830239922729956.472546652
722696.449085804730955.772926592
#Sta/Elev= 30
8662.888264.44768717.111 261.2328777.173265.53478948.298264.73229089.249255.6926
9149.657248.22549300.676239.95069431.559240.34859512.103244.57599703.394246.6303
 9723.53247.29699743.666252.05899783.951252.7366 9834.34247.21989894.807246.0521
 9925.04232.60579985.507228.310710066.13233.464110116.52250.693710155.38252.9542
10180.61256.219610205.84264.162510233.77265.7054 10604.1275.752310952.64273.4508
11072.45278.689611094.23277.706611126.91269.981111181.37280.522111236.67284.3355
#Mann= 3 , 0 , 0
8662.888  0.0736       08662.888  0.0736       011236.67  0.0736       0
#XS Ineff= 2 , 0
       09799.551         10190.1       0
Bank Sta=8662.888,11236.67
Exp/Cntr=0.3,0.1

Type RM Length L Ch R = 1 ,13383.09,642.097200,642.097200,642.097200
XS GIS Cut Line= 4
723178.297596037728433.742283285722957.344128817728964.805879995
722646.233017683  729475.9169911721837.877811597730460.580122808
#Sta/Elev= 30
8762.255259.88318796.111260.85848817.773256.21028861.097263.15458936.914262.3734
  9001.9253.83499175.195249.69939196.857247.34739218.519238.94529240.181235.6441
9361.091236.11299396.212241.15049765.079240.73789794.246234.64749829.366233.1297
 9852.78224.98219934.728227.709610012.24221.156210025.18 225.74810038.12236.9737
10063.83239.275710594.46246.746710599.67246.180810615.43232.596410631.19230.6164
10788.53237.459610804.55247.888410820.31249.9722 11150.8255.271911209.77252.2041
#Mann= 3 , 0 , 0
8762.255  0.0447       08762.255  0.0447       011209.77  0.0447       0
#XS Ineff= 2 , 0
       09402.662        10228.44       0
Bank Sta=8762.255,11209.77
Exp/Cntr=0.3,0.1