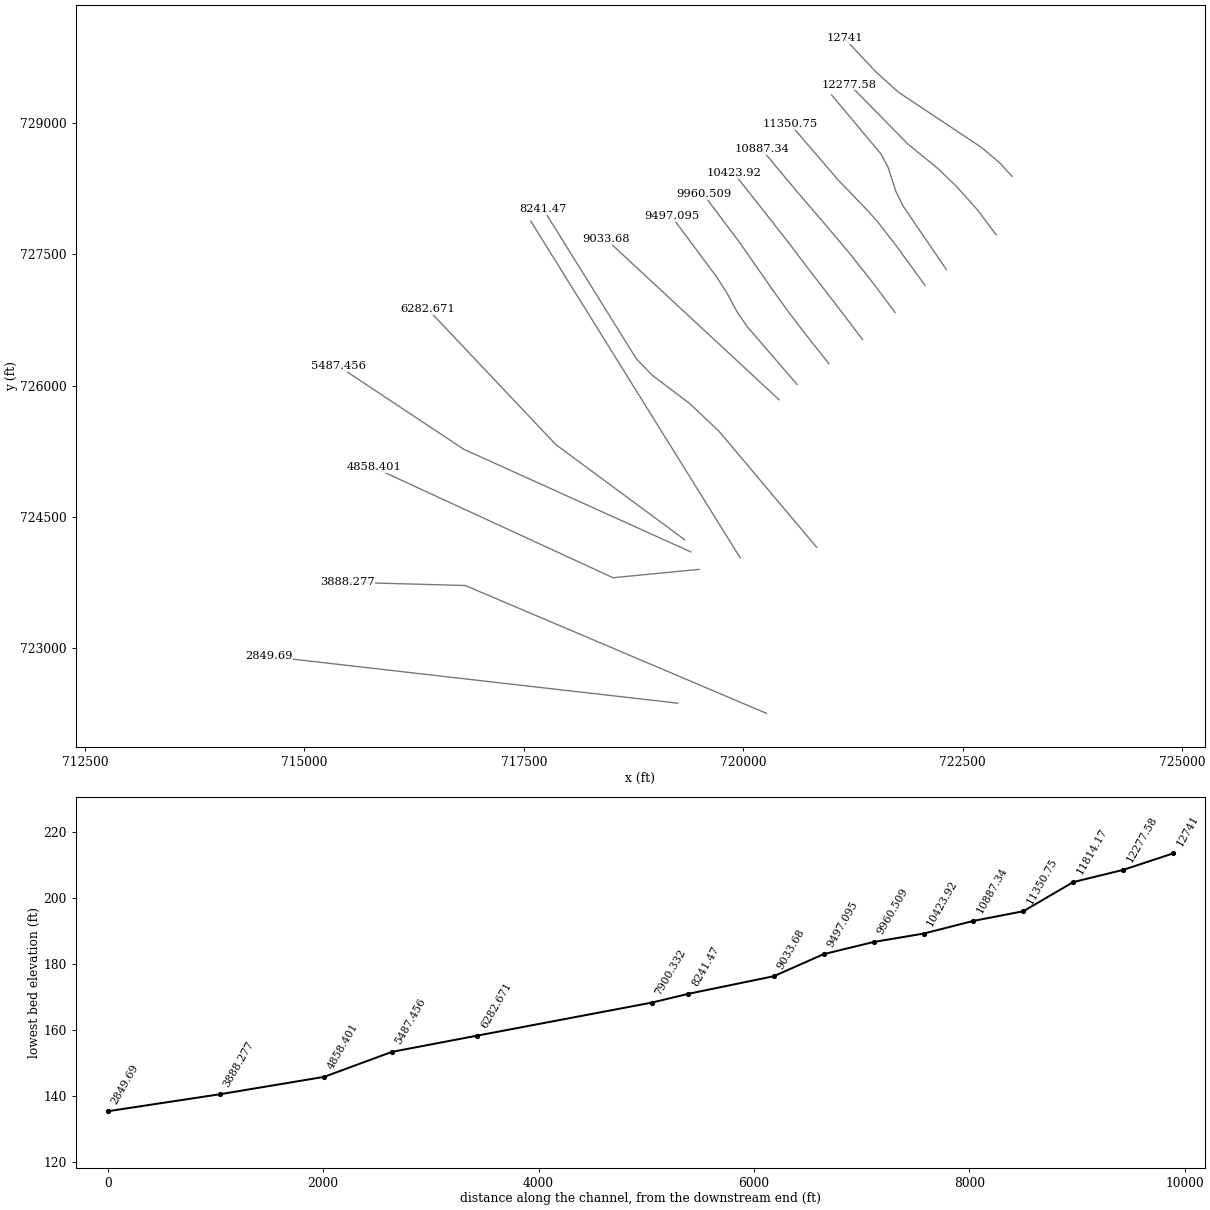
HEC-RAS study 4828_ras.prj: 4828

--- 4828_ras.g01 (geometry) --- (continued)

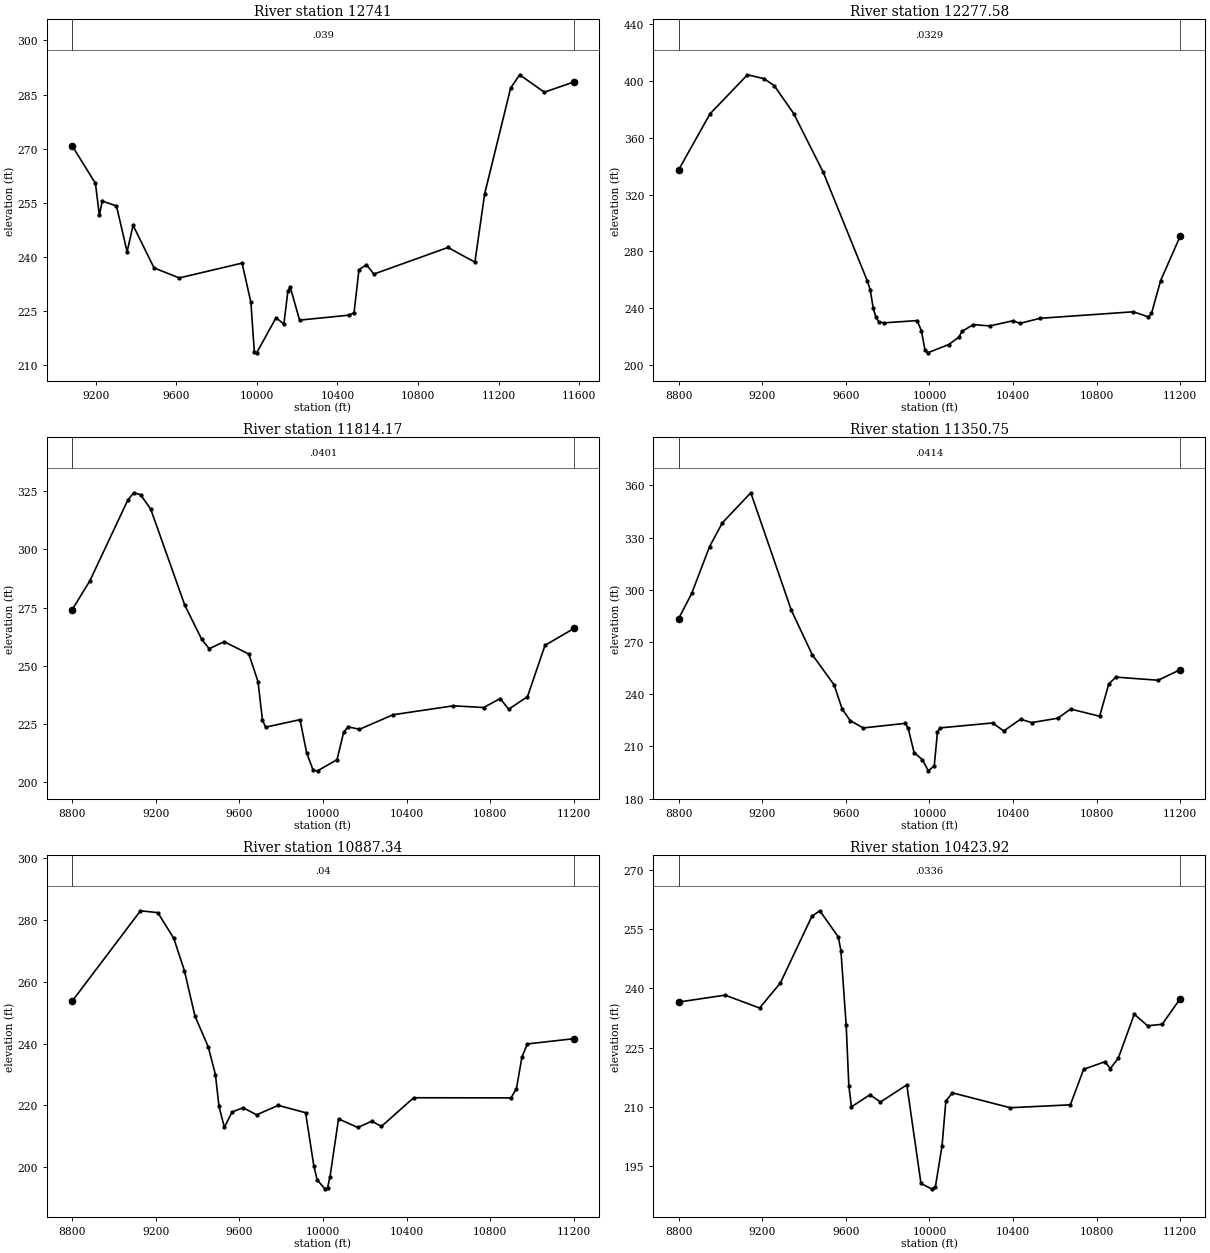
Type RM Length L Ch R = 1 ,   12741,463.414600,463.414600,463.414600
XS GIS Cut Line= 6
723064.917391777728387.880627617722921.111779779728543.650677279
722718.081711024728716.983305052721767.519002676 729350.48333551
721505.171561062729588.318204239 721154.26264025729964.693470032
#Sta/Elev= 30
9082.257 270.864 9198.54260.39249217.608251.56719232.039255.51199302.643254.1819
9355.557241.4835 9385.16248.80189489.169237.01319614.429234.23619926.262238.3375
9970.269227.44459987.254213.7025    9999213.494510095.19 223.24110133.92221.4197
10153.96230.739110165.55 231.67110211.89222.5509 10458.2223.936110482.39224.6184
10506.66236.503810543.83237.8778   10581 235.30710948.75242.675811082.38238.5894
11130.67257.480911259.76286.8048 11304.6290.488511426.94285.662911573.71288.5016
#Mann= 3 , 0 , 0
9082.257   0.039       09082.257   0.039       011573.71   0.039       0
#XS Ineff= 2 , 0
       09486.952        10772.96       0
Bank Sta=9082.257,11573.71
Exp/Cntr=0.3,0.1

Type RM Length L Ch R = 1 ,12277.58,463.414700,463.414700,463.414700
XS GIS Cut Line= 6
722881.845409042727721.924999282722665.748254134728011.025524397
722422.025368395728283.100110055722212.482952284728483.137462362
721876.861255387728757.274715533721210.210414922729436.992304973
#Sta/Elev= 30
8799.056337.31198949.832376.86969128.972404.35919207.996401.64949257.047396.7531
9350.295377.01869491.921335.62989703.372258.94129716.928 252.6149730.485240.3509
9744.041233.52039758.749230.1783 9784.71229.64399941.119231.23389961.431224.1381
9978.716 210.4719991.249208.504710091.94214.336910140.54219.4768   10156223.6749
10210.69 228.38810288.44227.444510399.85231.097710434.04229.280210529.17232.8324
10976.38 237.42511048.35233.782411062.91236.240711106.61259.358911200.97290.8923
#Mann= 3 , 0 , 0
8799.056  0.0329       08799.056  0.0329       011200.97  0.0329       0
#XS Ineff= 2 , 0
       0                10750.73       0
Bank Sta=8799.056,11200.97
Exp/Cntr=0.3,0.1

Type RM Length L Ch R = 1 ,11814.17,463.414600,463.414600,463.414600
XS GIS Cut Line= 6
722313.999352822727326.622335629721824.342035328728045.654616698
721740.343725189728215.814305281721649.262239284 728496.93684065
721564.819590607728651.072878183721007.255588485729318.142906934
#Sta/Elev= 30
8799.086274.01358884.552286.56169065.618321.18889093.859 324.3719126.643323.5725
9175.463317.3636 9338.05276.16199419.498261.37629455.433257.32689527.302260.3187
9645.064255.02929689.014243.21719710.195226.79049725.203223.58029890.028226.8108
9921.802212.63989953.167204.99529973.913204.807110067.41209.6154 10099.1221.4383
10120.37223.722810174.85222.669310335.55228.9278   10624232.766810768.92232.0338
10848.45235.8653 10888.7231.305810978.88236.677811062.77258.772311200.94266.0136
#Mann= 3 , 0 , 0
8799.086  0.0401       08799.086  0.0401       011200.94  0.0401       0
#XS Ineff= 2 , 0
       0                10702.25       0
Bank Sta=8799.086,11200.94
Exp/Cntr=0.3,0.1

Type RM Length L Ch R = 1 ,11350.75,463.414600,463.414600,463.414600
XS GIS Cut Line= 6
  722071.6139998727144.002823563   721744.934276727595.275109654
721534.967675483 727866.41805457721429.436374522727986.643794598
721085.387250161728344.140119772720534.616977364728985.856551076
#Sta/Elev= 30
8799.023283.33458862.128297.94338947.582324.82049008.972338.5195 9144.92355.7633
9339.131288.20049438.793262.78319544.035245.33199582.113231.53029620.505224.8377
9683.026 220.615 9884.67223.26549898.603220.30929926.468206.45859965.995 202.428
9994.718195.9682 10023.2198.869310038.31218.267910051.63220.656810301.94223.4815
10355.89218.881610436.14225.637610489.26223.6924 10614.2226.204310675.88231.4679
10814.72227.351710858.41245.819210891.85249.8369 11094.8248.030711200.98254.1415
#Mann= 3 , 0 , 0
8799.023  0.0414       08799.023  0.0414       011200.98  0.0414       0
#XS Ineff= 2 , 0
       0                10532.54       0
Bank Sta=8799.023,11200.98
Exp/Cntr=0.3,0.1

Type RM Length L Ch R = 1 ,10887.34,463.414600,463.414600,463.414600
XS GIS Cut Line= 6
721730.468043903726835.599435912721478.020561051727173.897219734
721220.575480147727499.363404807721055.757995823727697.553642098
 720578.79372036728256.002408168720212.520996204728696.258269552
#Sta/Elev= 30
8799.011253.7111 9126.52282.9718 9209.54282.35979285.872274.0535 9336.55263.6436
9387.227 248.9529451.009238.93339485.261229.94949502.298 219.6889527.943212.9448
9565.143217.9002  9617.7219.27759682.467216.97899785.594220.04079916.817217.6617
9956.249200.48599972.097195.965910008.78193.042610021.94193.342710033.77196.9958
10074.55215.669410166.62 212.88210233.89214.926410280.07213.237510434.01222.5027
10900.17222.457610926.18225.4506 10952.2 235.58810978.22239.906411200.99241.6044
#Mann= 3 , 0 , 0
8799.011    0.04       08799.011    0.04       011200.99    0.04       0
#XS Ineff= 2 , 0
       0                10598.47       0
Bank Sta=8799.011,11200.99
Exp/Cntr=0.3,0.1

Type RM Length L Ch R = 1 ,10423.92,463.414700,463.414700,463.414700
XS GIS Cut Line= 6
 721359.83573323726527.471157324721104.360828439726863.502137811
720694.095309552727396.693975164720546.253172149727594.566091569
720245.488718255727979.614367889719891.123088847728427.984506401
#Sta/Elev= 30
8799.009236.55099022.019238.30599187.026235.03449286.106241.36869437.518258.3137
9475.371 259.6999563.695253.07239576.312249.55839601.548230.64649614.165215.3531
9626.783209.97799715.107213.04539765.577211.20399891.754215.54339959.509190.5449
10010.05189.1876 10028.5189.686510060.61200.173310078.53211.447310110.03213.5333
10386.62209.7567 10674.6210.492210738.33219.5091 10840.3221.422310865.79219.6722
10904.45222.363310980.51 233.47411044.24230.540511114.11230.9091   11201237.4496
#Mann= 3 , 0 , 0
8799.009  0.0336       08799.009  0.0336       0   11201  0.0336       0
#XS Ineff= 2 , 0
       0                10691.33       0
Bank Sta=8799.009,11201
Exp/Cntr=0.3,0.1

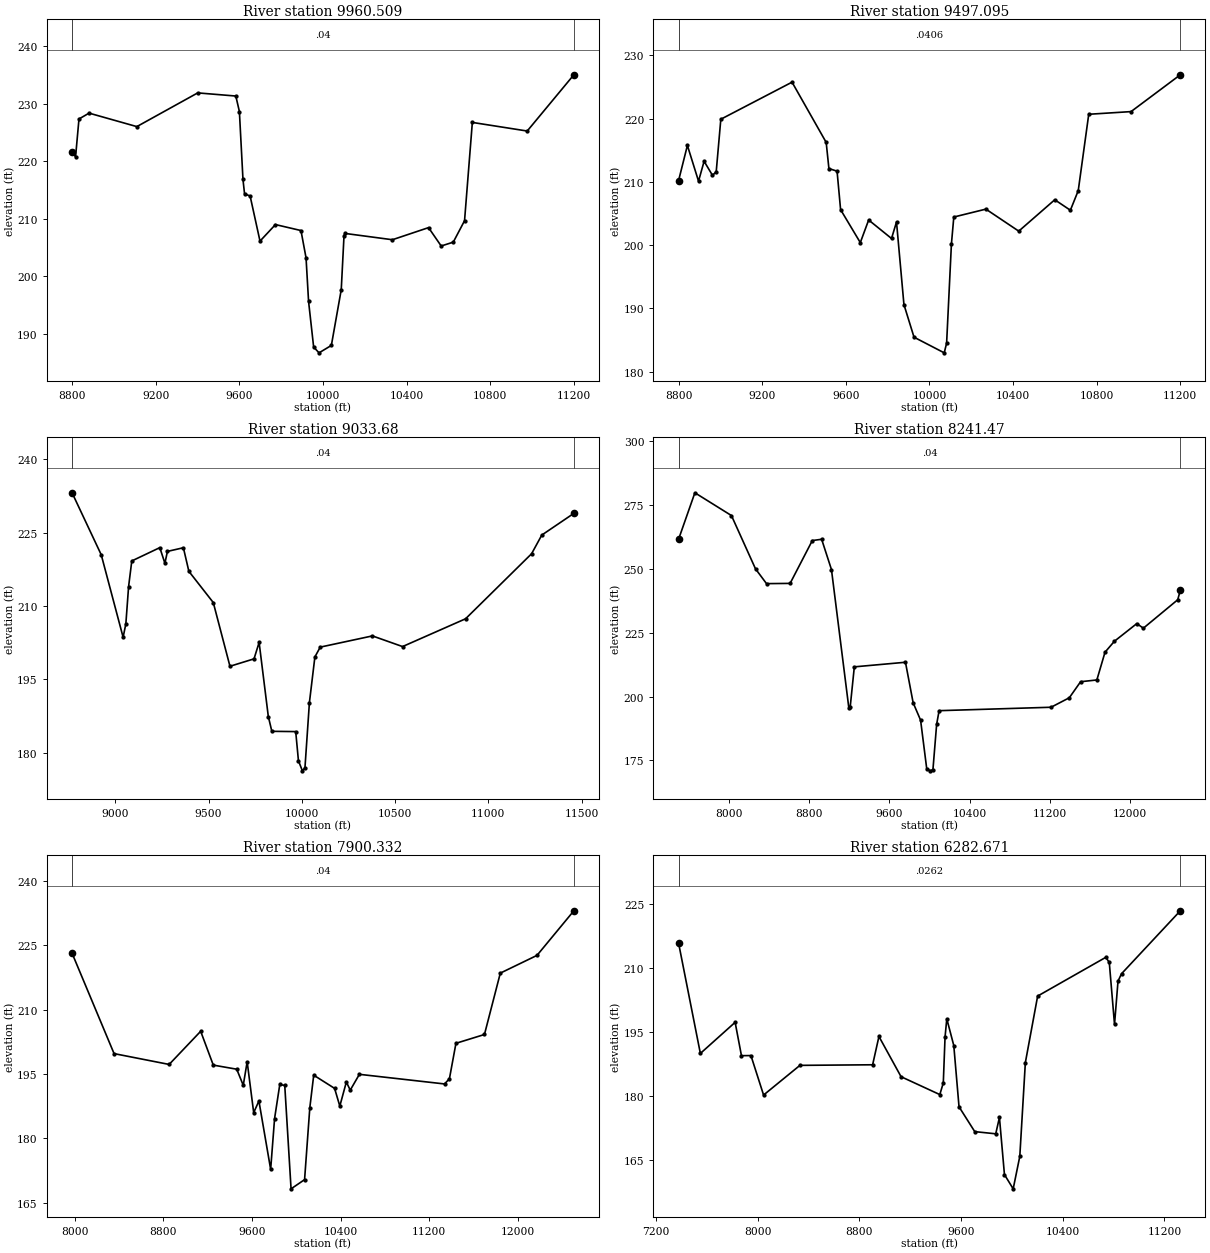
Type RM Length L Ch R = 1 ,9960.509,463.414600,463.414600,463.414600
XS GIS Cut Line= 6
720975.525454928 726251.87412058 720713.61607389 726582.91478095
720508.389931557726852.455527798720350.709530444727071.378435812
719954.339725293 727641.09571395719547.783964203728182.665605538
#Sta/Elev= 30
8799.016221.64688815.753220.76438832.097227.35648880.447228.37289109.032226.0273
9400.507 231.896 9582.83231.3495 9599.94228.65699617.051216.85039624.674214.3142
9651.271213.95019698.617206.0923 9772.56208.97379894.742207.93339918.995203.1861
9931.122195.58639955.376187.65069981.231 186.644 10040.2187.936910087.53197.6454
10100.77 207.03110105.25207.432610332.43 206.33410505.34208.441610565.91205.2453
10623.74205.911710677.74209.647410715.02226.755610977.69225.256611200.98235.0494
#Mann= 3 , 0 , 0
8799.016    0.04       08799.016    0.04       011200.98    0.04       0
#XS Ineff= 2 , 0
       0                               0
Bank Sta=8799.016,11200.98
Exp/Cntr=0.3,0.1

Type RM Length L Ch R = 1 ,9497.095,463.414600,463.414600,463.414600
XS GIS Cut Line= 6
720614.258069718726013.184511048720046.885270036726672.595496793
719932.211173285726839.654078156719816.235976248727054.504339533
 719692.78435522727247.782443183719182.452246404727934.288302155
#Sta/Elev= 30
8799.056210.18158841.469215.77548894.793210.12028921.455213.26788961.447211.0493
  8979.4211.6033 9001.44219.91719342.331225.78249505.828216.25229518.847212.1175
9557.904211.70189574.789 205.6169669.144200.4015  9709.1203.97989818.564201.0528
9842.422203.66759878.004190.59779926.281185.438110070.82182.965610082.28184.4973
 10105.2200.150910116.68204.447410270.23205.698910427.57202.215810599.92207.1795
 10674.7205.522710712.36208.626510762.56220.702910965.09221.125511200.97226.9502
#Mann= 3 , 0 , 0
8799.056  0.0406       08799.056  0.0406       011200.97  0.0406       0
#XS Ineff= 2 , 0
       09384.298        10844.39       0
Bank Sta=8799.056,11200.97
Exp/Cntr=0.3,0.1

Type RM Length L Ch R = 1 , 9033.68,792.209800,792.209800,792.209800
XS GIS Cut Line= 2
720409.524643511725838.679940432718439.038532376727670.277162641
#Sta/Elev= 30
8768.443233.14948924.802220.47099042.112203.59999056.801206.33549071.489 213.967
9088.636219.20589238.817221.92839266.123218.73739279.776221.15999365.251 221.907
9394.627217.08429525.527210.69619614.949197.66149743.972199.17969771.278202.5391
9820.583187.38489839.542184.35529967.464184.29969982.152178.320610003.38176.2723
10017.03176.8849 10040.9190.233910070.28199.571110098.95201.578410378.73203.8721
 10540.3201.690810878.13207.374911232.13220.680211286.74224.497311458.72228.9399
#Mann= 3 , 0 , 0
8768.443    0.04       08768.443    0.04       011458.72    0.04       0
#XS Ineff= 2 , 0
       09450.086        10474.07       0
Bank Sta=8768.443,11458.72
Exp/Cntr=0.3,0.1

Type RM Length L Ch R = 1 , 8241.47,341.138600,341.138600,341.138600
XS GIS Cut Line= 6
720837.262991351724154.386624671 719723.80067422725480.618541806
719384.573755173725800.584556338718963.110019259  726119.2682953
718784.445344999726304.484653882717720.681363742728016.485531638
#Sta/Elev= 30
7499.048 261.5067661.998279.73878026.452270.82598266.243249.98028376.005244.1934
 8611.21244.28418832.605 261.0468925.567261.54989023.419249.69469196.148195.7135
9209.828195.79669251.344211.63259761.087213.43079837.747197.56549911.814190.7842
9973.504171.623710010.46170.949310035.02171.416610071.87189.153510096.44194.4872
11212.25 195.82811394.29199.536311506.86205.815411668.93206.505511750.26 217.365
11843.68221.644712067.24228.562512132.49226.754912475.03 237.88712500.94241.6244
#Mann= 3 , 0 , 0
7499.048    0.04       07499.048    0.04       012500.94    0.04       0
#XS Ineff= 2 , 0
       09616.674        10535.21       0
Bank Sta=7499.048,12500.94
Exp/Cntr=0.3,0.1

Type RM Length L Ch R = 1 ,7900.332,1617.660600,1617.660600,1617.660600
XS GIS Cut Line= 2
719966.816310167 724033.12438488717579.663532376 727878.61049597
#Sta/Elev= 30
7978.029223.12058356.879199.75098853.658197.23189138.066204.9492 9251.83197.0748
9463.269196.12269522.119192.37539557.429197.8528 9616.28186.0061 9663.36188.7291
9769.291172.80729804.601184.62579851.682192.56439896.489192.33429953.371168.2729
10075.31170.414810122.39187.1298 10157.7194.732310346.03191.657110393.11187.5335
10451.96193.139110487.27191.249810569.66194.929311337.49192.689311381.79193.9023
11440.65202.151311697.74204.202111840.83218.488212171.76222.6193 12504.2233.0005
#Mann= 3 , 0 , 0
7978.029    0.04       07978.029    0.04       0 12504.2    0.04       0
#XS Ineff= 2 , 0
       09650.962         10563.3       0
Bank Sta=7978.029,12504.2
Exp/Cntr=0.3,0.1

Type RM Length L Ch R = 1 ,6282.671,795.214800,795.214800,795.214800
XS GIS Cut Line= 3
719333.135754645724241.457718194717866.121865749725326.527162656
716407.788532346726871.666051537
#Sta/Elev= 30
7375.954215.90137547.769189.99567821.408197.28667871.161189.4744 7945.79 189.501
8045.295180.25518331.372187.20628903.527187.34268953.279193.96629127.413184.5476
9432.308180.36149459.809183.10059473.559193.8404 9487.31198.10649542.313191.8542
9583.564177.4976 9707.32171.68579872.461171.17429901.599174.99859941.081161.6244
10009.83158.284710061.86165.888410105.57187.847210202.34203.435510738.62212.5077
10766.12211.325710807.37196.794910834.87206.938210862.37208.659911325.31223.4125
#Mann= 3 , 0 , 0
7375.954  0.0262       07375.954  0.0262       011325.31  0.0262       0
#XS Ineff= 2 , 0
       08890.481         10224.1       0
Bank Sta=7375.954,11325.31
Exp/Cntr=0.3,0.1

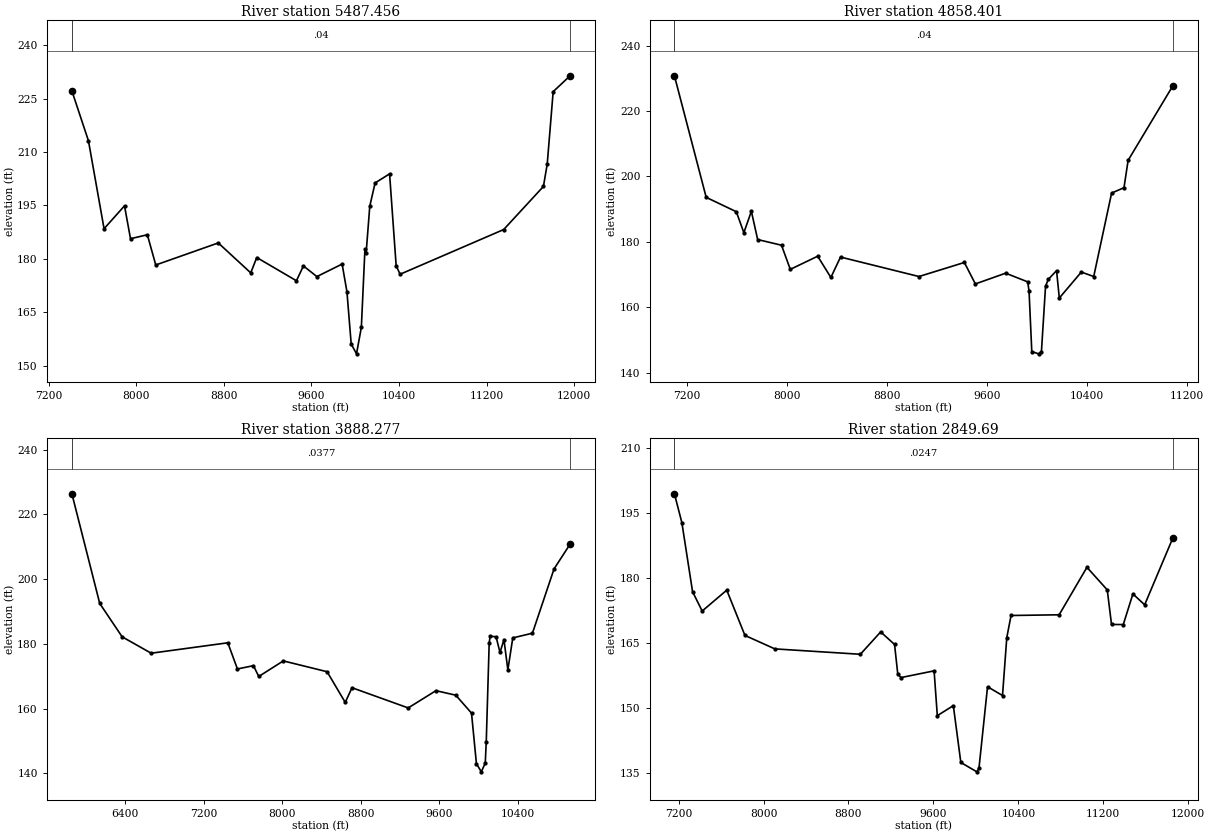
Type RM Length L Ch R = 1 ,5487.456,629.054900,629.054900,629.054900
XS GIS Cut Line= 3
719402.580199033724102.568829313716815.774643481725274.443829298
715392.163532406726220.624384865
#Sta/Elev= 30
7412.744227.18567564.037213.15597706.501188.47787893.132194.90177948.024185.6667
 8101.72186.78318178.568178.29468749.438184.48549045.852176.07979100.743180.3896
9463.027173.86439526.954178.02699649.658175.03529880.202178.55089924.115170.8059
9963.158156.097510011.63153.344610055.85 160.80910088.79182.850510099.77181.7609
 10132.7194.791410181.26201.330510313.58203.879410373.62178.091710409.64175.6896
11355.64188.246911718.43200.346511753.09206.640911807.29226.963611961.98231.4194
#Mann= 3 , 0 , 0
7412.744    0.04       07412.744    0.04       011961.98    0.04       0
#XS Ineff= 2 , 0
       09161.851        10176.28       0
Bank Sta=7412.744,11961.98
Exp/Cntr=0.3,0.1

Type RM Length L Ch R = 1 ,4858.401,970.124500,970.124500,970.124500
XS GIS Cut Line= 3
719498.066310167723902.916051522718517.163532376723807.429940417
715791.469087958725066.110495985
#Sta/Elev= 30
 7100.99 230.7667355.252193.59987596.387189.2115 7656.67182.79777716.954189.3301
 7767.19180.70657958.088178.96878028.419171.58918247.701175.60868353.266169.1061
8430.369175.35259058.209169.40019421.695173.69559509.813 167.1349752.137170.4242
9928.373167.77079939.388165.02159961.417 146.45310016.49145.766210038.52 146.392
10071.56 166.46510093.59168.532510159.68 171.20810181.71162.823810357.95170.7609
10457.08169.402910600.27194.9102 10699.4196.561110732.45204.917411088.81227.5969
#Mann= 3 , 0 , 0
 7100.99    0.04       0 7100.99    0.04       011088.81    0.04       0
#XS Ineff= 2 , 0
       09236.409        10292.49       0
Bank Sta=7100.99,11088.81
Exp/Cntr=0.3,0.1

Type RM Length L Ch R = 1 ,3888.277,1038.586800,1038.586800,1038.586800
XS GIS Cut Line= 3
720265.803704441722259.120112643716833.736424476723718.485117301
 715491.61082986723755.766383797
#Sta/Elev= 30
5858.645226.33966142.048 192.4866370.244182.17666665.887177.11537446.027180.3315
7543.826172.25457706.823173.26797761.156 169.9358011.085174.73988456.611171.4028
8641.342161.92928710.313166.46149282.465160.22069564.994  165.559766.905164.1549
9926.967158.62689976.986143.004810027.01140.490110067.02143.235110077.02149.7142
10107.04180.349810117.04182.377510177.06182.184110217.08177.342110257.09 181.312
10297.11171.965210347.13181.840310547.21183.292910767.29203.142310930.74210.8043
#Mann= 3 , 0 , 0
5858.645  0.0377       05858.645  0.0377       010930.74  0.0377       0
#XS Ineff= 2 , 0
       0  8992.5                       0
Bank Sta=5858.645,10930.74
Exp/Cntr=0.3,0.1

Type RM Length L Ch R = 1 , 2849.69,853.680300,853.680300,853.680300
XS GIS Cut Line= 2
719254.631663173722375.558050454 714593.17332986722909.412217125
#Sta/Elev= 30
7160.933199.4064 7231.02192.75257331.674176.85967422.262172.39237653.765177.2071
7824.877166.78068106.707163.67538911.936162.43599103.178167.58369234.028164.6986
9264.224 157.876 9294.42157.06759606.447158.62029636.643148.29549787.623150.6005
9858.081137.512510009.06135.354210029.19136.234910109.71154.958310250.63152.9372
10290.89166.269810331.15171.368810784.09171.531511045.79182.469411237.04177.2721
 11277.3169.302411388.02169.2815 11478.6176.338711589.32173.829711852.86189.1138
#Mann= 3 , 0 , 0
7160.933  0.0247       07160.933  0.0247       011852.86  0.0247       0
#XS Ineff= 2 , 0
       0                               0
Bank Sta=7160.933,11852.86
Exp/Cntr=0.3,0.1