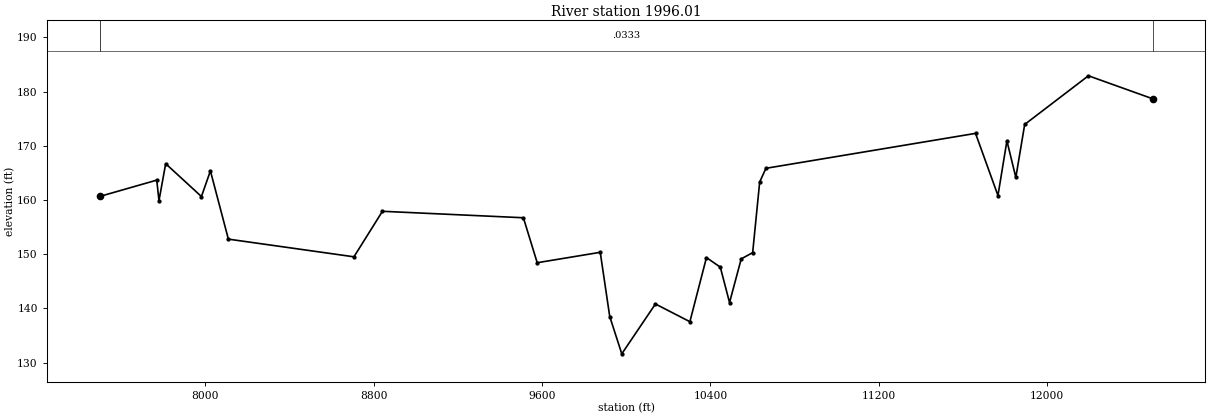
HEC-RAS study 4828_ras.prj: 4828

--- 4828_ras.g01 (geometry) --- (continued)

Type RM Length L Ch R = 1 , 1996.01,0.000000,0.000000,0.000000
XS GIS Cut Line= 6
718830.674589679720936.234379883717837.749622742721299.399360111
717064.548512613721615.509158873  715147.3661116722530.060756579
714675.209196873722699.318582127714207.140606892722815.048782723
#Sta/Elev= 30
7499.053160.6499  7770.3163.6625 7780.91159.88577812.737166.69587982.561160.6383
8025.202165.36988110.484 152.7818706.899149.51938842.275157.91569511.687156.7237
9577.388148.43029876.752  150.359921.817 138.5069979.047131.625310138.88140.8214
10302.46137.551810381.21149.379610446.99147.611310490.85141.085310546.33149.1396
10600.68150.288310633.97163.314110663.75165.844711659.23172.2851 11765.7160.8272
11808.25170.905711850.62 164.15911892.66173.931312195.36 182.90912500.96178.6619
#Mann= 3 , 0 , 0
7499.053  0.0333       07499.053  0.0333       012500.96  0.0333       0
#XS Ineff= 2 , 0
       0                               0
Bank Sta=7499.053,12500.96
Exp/Cntr=0.3,0.1